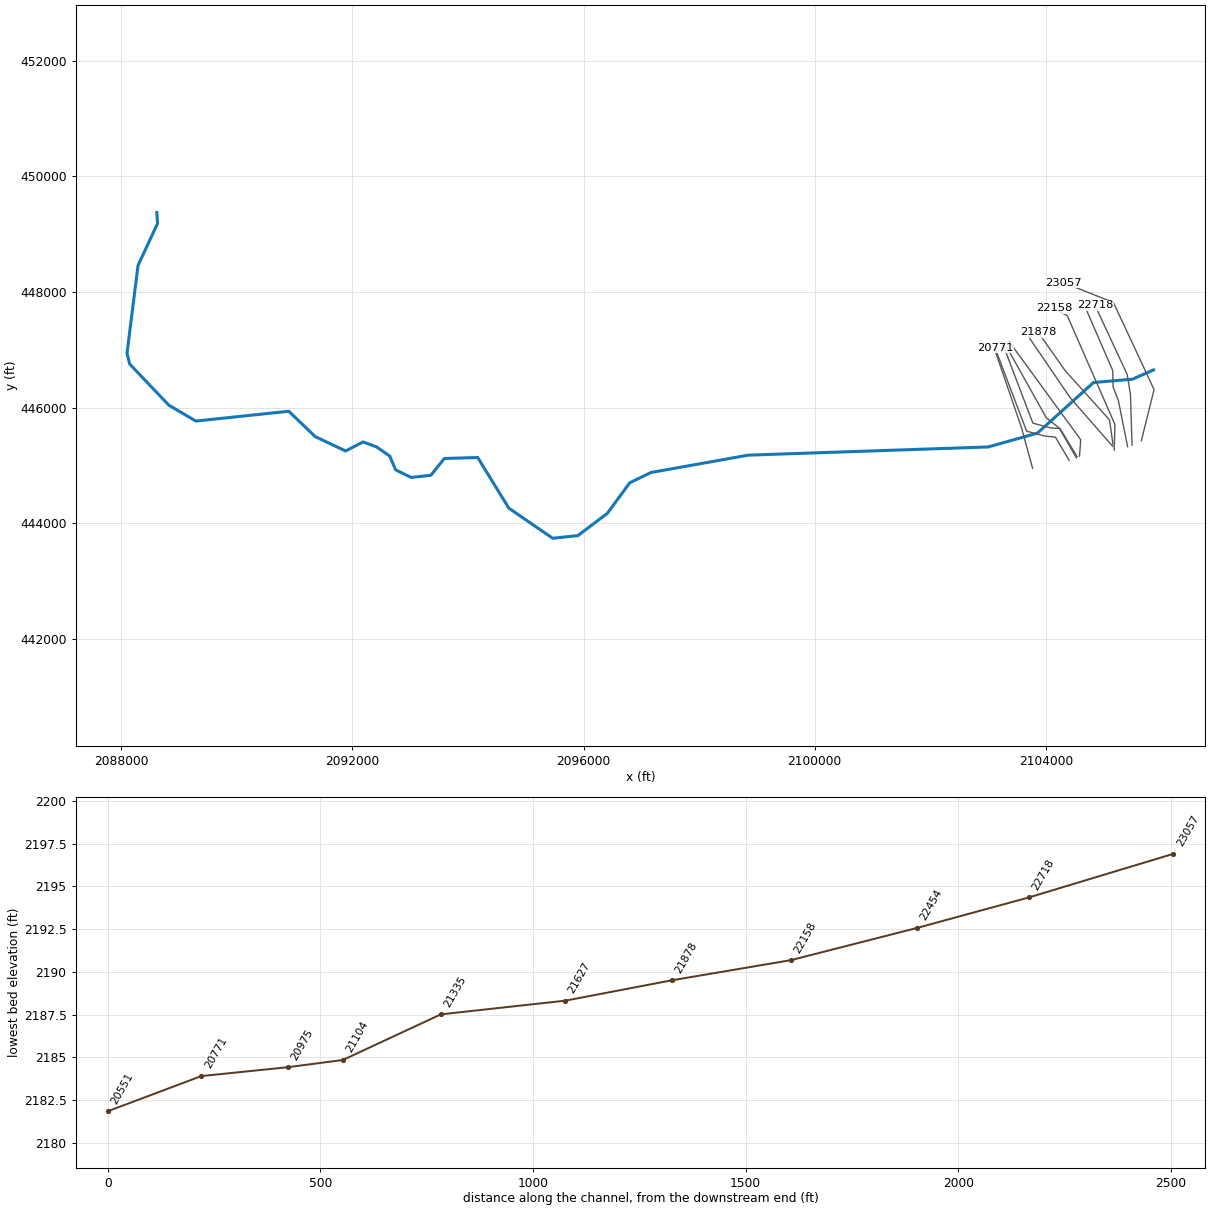
--- CHERRYRV.prj (project) ---

Proj Title=CHERRYRV
Current Plan=p03
Default Exp/Contr=0,0
English Units
Geom File=g03
Flow File=f03
Flow File=f05
Flow File=f06
Flow File=f01
Plan File=p02
Plan File=p03
Plan File=p04
Y Axis Title=Elevation
X Axis Title(PF)=Main Channel Distance
X Axis Title(XS)=Station
BEGIN DESCRIPTION:
Stream Name : Cherry River
Nicholas County, WV
WV Disaster Studies / PMR
WVDHSEM-2017-2, Flood Risk Project
HEC-RAS Version: HEC-RAS 5.0.3
Upstream Extents: 500 ft. downstream of Lower Johnstown Road
Downstream Extents: 1500 ft downstream of Nettle Fenwick Road
General Notes:  Hydrology- Gage 03189000 is located on the Cherry River study reach. PeakFQ was used to run bulletin 17C on the gage. The upstream from gage equation was used with Qk = Qs. The regression equation flow at the gage, Qr, was not considered.
Q101 was estimated using the 84% confidence upper limit of the 17C result for the flow point at the gage. The ratio of the 100 to 101 flow at the gage was applied to the ungaged locations to estimate the Q101.
Based off this analysis, the 10%, 4%, 2%, 1% and 1%plus frequency events were estimated using a 17C analysis.
Hydraulics: model was calibrated based on 2016 June Disaster HWM's obtained from USGS
END DESCRIPTION:
DSS Export Rating Curves= 0
DSS Export Rating Curve Sorted= 0
DSS Export Volume Flow Curves= 0
DXF Filename=.\Backup\CHERRYRV\CHERRYRV.
DXF OffsetX= 0
DXF OffsetY= 0
DXF ScaleX= 0
DXF ScaleY= 0

--- CHERRYRV.p03 (plan) ---

Plan Title=Multiprofile
Program Version=4.10
Short Identifier=Multiprofile
Geom File=g03
Flow File=f01
Subcritical Flow
K Sum by GR= 0
Std Step Tol= 0.01
Critical Tol= 0.01
Num of Std Step Trials= 20
Max Error Tol= 0.3
Flow Tol Ratio= 0.001
Split Flow NTrial= 30
Split Flow Tol= 0.02
Split Flow Ratio= 0.02
Log Output Level= 0
Friction Slope Method= 1
Unsteady Friction Slope Method= 2
Unsteady Bridges Friction Slope Method= 1
Parabolic Critical Depth
Global Vel Dist= 0 , 0 , 0
Global Log Level= 0
CheckData=True
Encroach Param=-1 ,0,0, 0
Run HTab= 0
Run UNet= 0
Run PostProcess= 0
Run WQNet= 0
UNET Theta= 0
UNET Theta Warmup= 0
UNET ZTol= 0
UNET ZSATol= 0
UNET MxIter= 0
UNET MaxInSteps= 0
UNET DtIC= 0
UNET DtMin= 0
UNET MaxCRTS= 0
UNET WFStab= 0
UNET SFStab= 0
UNET WFX= 1
UNET SFX= 1
UNET DSS MLevel= 1
UNET DZMax Abort= 0
UNET Convert EG Bridges= 0
UNET Use Existing IB Tables= 0
UNET Froude Reduction=False
UNET Froude Limit= 0
UNET Froude Power= 0
UNET Time Slicing=0,0, 5
UNET Junction Losses=0
DSS File=dss
Write IC File= 0
Write IC File at Sim End=0
Echo Input=False
Echo Parameters=False
Echo Output=False
Write Detailed= 0
WQ AD Non Conservative
WQ ULTIMATE=-1
WQ Max Comp Step=1HOUR
WQ Output Interval=15MIN
WQ Output Selected Increments= 0
WQ Output face flow=0
WQ Output face velocity=0
WQ Output face area=0
WQ Output face dispersion=0
WQ Output cell volume=0
WQ Output cell surface area=0
WQ Output cell continuity=0
WQ Output cumulative cell continuity=0
WQ Output face conc=0
WQ Output face dconc_dx=0
WQ Output face courant=0
WQ Output face peclet=0
WQ Output face adv mass=0
WQ Output face disp mass=0
WQ Output cell mass=0
WQ Output cell source sink temp=0
WQ Output cell source sink nsm=0
WQ Output MaxMinRange=-1
WQ Daily Max Min Mean=-1
WQ Daily Range=0
WQ Daily Time=0
WQ Create Restart=0
WQ Fixed Restart=0
WQ System Summary=0
WQ Use Fixed Temperature=0
Sorting and Armoring Iterations= 10
XS Update Threshold= 0.02
Hydraulics Update Threshold= 0.02
Energy Slope Method= 1
Volume Change Method= 0
XS Weighting Method= 0
Number of US Weighted Cross Sections= 1
Number of DS Weighted Cross Sections= 1
Upstream XS Weight=0.25
Main XS Weight=0.5
Downstream XS Weight=0.25
Number of DS XS's Weighted with US Boundary= 1
Upstream Boundary Weight= 1
Weight of XSs Associated with US Boundary= 0
Number of US XS's Weighted with DS Boundary= 1
Downstream Boundary Weight= 0.5
Weight of XSs Associated with DS Boundary= 0.5
Sediment Output Level= 4
Mass or Volume Output= 0
Output Increment Type= 1
Profile and TS Output Increment= 10
XS Output Flag= 0
XS Output Increment= 10
Disregard all LS=0
Disregard all Conn=0
Disregard all Breaches=0
Disregard all Pumps=0

--- CHERRYRV.p02 (plan) ---

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Plan Title=June16 Disaster
Program Version=5.03
Short Identifier=June16Disaster
Geom File=g03
Flow File=f05
Mapping Interval=1HOUR
Run Sediment= 0
Run RASMapper= 0
UNET Max Iter WO Improvement= 0
UNET Pardiso=0
UNET D1 Cores= 0
UNET D2 Coriolis=0
UNET D2 Cores= 0
UNET D2 Theta= 1
UNET D2 Theta Warmup= 1
UNET D2 Z Tol= 0.01
UNET D2 Volume Tol= 0.01
UNET D2 Max Iterations= 20
UNET D2 Equation= 0
UNET D2 RampUpFraction=0.1
UNET D2 TimeSlices= 1
UNET D2 BCVolumeCheck=0
UNET D1D2 MaxIter= 0
UNET D1D2 ZTol=0.01
UNET D1D2 QTol=0.1
UNET D1D2 MinQTol=1
Write IC File at Fixed DateTime=0
HDF Write Warmup=0
HDF Write Time Slices=0
HDF Flush=0
HDF Face Node Velocities=0
HDF Compression= 1
HDF Chunk Size= 1
HDF Spatial Parts= 1
HDF Use Max Rows=0
HDF Fixed Rows= 1
Calibration Method= 0
Calibration Iterations= 20
Calibration Max Change=0.05
Calibration Tolerance=0.2
Calibration Maximum=1.5
Calibration Minimum=0.5
Calibration Optimization Method= 1
WQ Output nsm pathways=0
WQ Output nsm derived pathways=0
WQ Write To DSS=0
Bed Roughness Predictor= 0
Sediment Retention Method= 0
Percentile Method= 0
Write Gradation File= 0
Read Gradation Hotstart= 0
Write HDF5 File= 1
Write DSS Sediment File= 0
SV Curve= 0
Specific Gage Flag= 0

--- CHERRYRV.p04 (plan) ---

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Plan Title=Floodway
Program Version=5.07
Short Identifier=Floodway
Geom File=g03
Flow File=f03
Encroach Param= 0 ,0,0, 2
Encroach River=CHERRYRV
Encroach Reach=Main
Encroach Node=23057
       1  1112.7    1305
Encroach Node=22718
       1    1075    1187
Encroach Node=22454
       1    1050    1261
Encroach Node=22158
       1    1192    1325
Encroach Node=21878
       1     990    1210
Encroach Node=21627
       1     716    1235
Encroach Node=21335
       1     520    1250
Encroach Node=21104
       1     530    1390
Encroach Node=20975
       1     560    1555
Encroach Node=20771
       1     720    1550
Encroach Node=20551
       1     522    1142
Encroach Node=20415
       1     520    1120
Encroach Node=20295
       1   495.7    1130
Encroach Node=20113
       1     502    1380
Encroach Node=19881
       1   518.5    1470
Encroach Node=19694
       1     619    1590
Encroach Node=19490
       1     626    1460
Encroach Node=19388
       1     592    1436
Encroach Node=19251
       1     622    1436
Encroach Node=19022
       1   704.5    1400
Encroach Node=18616
       1     740    1350
Encroach Node=18198
       1     650    1200
Encroach Node=17501
       1     910    1335
Encroach Node=16757
       1     800    1390
Encroach Node=15707
       1     750    1280
Encroach Node=14867
       1     850    1300
Encroach Node=14057
       1    1190    1450
Encroach Node=13878
       1  1220.2    1430
Encroach Node=13385
       1    1100    1350
Encroach Node=12625
       1    1602    1750
Encroach Node=11640
       1    1462    1630
Encroach Node=10893
       1   774.2    1060
Encroach Node=10359
       1     896    1293
Encroach Node=9677
       1    1224    1377
Encroach Node=8884
       1   634.8    1050
Encroach Node=8500
       1     522     840
Encroach Node=7727
       1     747    1004
Encroach Node=6837
       1     771     965
Encroach Node=6479
       1   892.2    1160
Encroach Node=5872
       1    1253    1392
Encroach Node=5177
       1    1226    1370
Encroach Node=4579
       1     790    1130
Encroach Node=3830
       1     728     980
Encroach Node=3377
       1     764     985
Encroach Node=2951
       1     715     925
Encroach Node=2773
       1  842.79    1092
Encroach Node=2287
       1     842    1030
Encroach Node=1865
       1    1240    1500
Encroach Node=1673
       1    1038    1250
Encroach Node=1490
       1 1024.84 1260.76
Encroach Node=1123
       1     725     865
Encroach Node=689
       1     775    1100
Encroach Node=386
       1     828    1105
Encroach Node=54
       1     711    1018
Computation Interval=0.1SEC
Output Interval=1MIN
Instantaneous Interval=Max Profile
Mapping Interval=1HOUR
Computation Time Step Use Courant=        0
Computation Time Step Use Time Series=    0
Computation Time Step Count To Double=0
Computation Time Step Max Doubling=0
Computation Time Step Max Halving=0
Computation Time Step Residence Courant=0
Run Sediment= 0
Run RASMapper= 0
UNET Max Iter WO Improvement= 0
UNET 1D Methodology=Finite Difference
UNET Pardiso=0
UNET D1 Cores= 0
UNET D2 Coriolis=0
UNET D2 Cores= 0
UNET D2 Theta= 1
UNET D2 Theta Warmup= 1
UNET D2 Z Tol= 0.01
UNET D2 Volume Tol= 0.01
UNET D2 Max Iterations= 20
UNET D2 Equation= 0
UNET D2 RampUpFraction=0.1
UNET D2 TimeSlices= 1
UNET D2 BCVolumeCheck=0
UNET D1D2 MaxIter= 0
UNET D1D2 ZTol=0.01
UNET D1D2 QTol=0.1
UNET D1D2 MinQTol=1
Write IC File at Fixed DateTime=0
HDF Write Warmup=0
HDF Write Time Slices=0
HDF Flush=0
HDF Face Node Velocities=0
HDF Compression= 1
HDF Chunk Size= 1
HDF Spatial Parts= 1
HDF Use Max Rows=0
HDF Fixed Rows= 1
Calibration Method= 0
Calibration Iterations= 20
Calibration Max Change=0.05
Calibration Tolerance=0.2
Calibration Maximum=1.5
Calibration Minimum=0.5
Calibration Optimization Method= 1
WQ Output nsm pathways=0
WQ Output nsm derived pathways=0
WQ Write To DSS=0
Bed Roughness Predictor= 0
Sediment Retention Method= 0
Percentile Method= 0
Write Gradation File= 0
Read Gradation Hotstart= 0
Write HDF5 File= 1
Write Binary Output= 1
Write DSS Sediment File= 0
SV Curve= 0
Specific Gage Flag= 0

--- CHERRYRV.f01 (steady flow) ---

Flow Title=Gage-Based Flows
Program Version=4.10
Number of Profiles= 6
Profile Names=P100yr,P10yr,P25yr,P50yr,P100yrPLUS,P500yr
River Rch & RM=CHERRYRV,Main            ,23057
   24148   11558   15825   19715   33704   37937
River Rch & RM=CHERRYRV,Main            ,11640
   28085   13500   18445   22929   39199   43933
River Rch & RM=CHERRYRV,Main            ,2287
   35300   17080   23260   28820   49270   54860
Boundary for River Rch & Prof#=CHERRYRV,Main            , 1
Up Type= 0
Dn Type= 1
Dn Known WS=2097.5
Boundary for River Rch & Prof#=CHERRYRV,Main            , 2
Up Type= 0
Dn Type= 1
Dn Known WS=2094.1
Boundary for River Rch & Prof#=CHERRYRV,Main            , 3
Up Type= 0
Dn Type= 1
Dn Known WS=2095.2
Boundary for River Rch & Prof#=CHERRYRV,Main            , 4
Up Type= 0
Dn Type= 1
Dn Known WS=2096.5
Boundary for River Rch & Prof#=CHERRYRV,Main            , 5
Up Type= 0
Dn Type= 1
Dn Known WS=2101
Boundary for River Rch & Prof#=CHERRYRV,Main            , 6
Up Type= 0
Dn Type= 1
Dn Known WS=2100.5
Observed WS=CHERRYRV        ,Main            ,23053.8 ,0,2218.6,,,,,
Observed WS=CHERRYRV        ,Main            ,22450   ,0,2206.1,,,,,
Observed WS=CHERRYRV        ,Main            ,22154.2 ,0,2206.1,,,,,
Observed WS=CHERRYRV        ,Main            ,21624   ,0,2204,,,,,
Observed WS=CHERRYRV        ,Main            ,21117   ,0,2201.8,,,,,
Observed WS=CHERRYRV        ,Main            ,20411.4 ,0,2197.9,,,,,
Observed WS=CHERRYRV        ,Main            ,20109.9 ,0,2197.4,,,,,
Observed WS=CHERRYRV        ,Main            ,19018.1 ,0,2190.8,,,,,
Observed WS=CHERRYRV        ,Main            ,18195   ,0,2186.6,,,,,
Observed WS=CHERRYRV        ,Main            ,15703.3 ,0,2180,,,,,
Observed WS=CHERRYRV        ,Main            ,14863.1 ,0,2178,,,,,
Observed WS=CHERRYRV        ,Main            ,13381.7 ,0,2174.6,,,,,
Observed WS=CHERRYRV        ,Main            ,12621.1 ,0,2171.6,,,,,
Observed WS=CHERRYRV        ,Main            ,3826.5  ,0,2121.7,,,,,
Observed WS=CHERRYRV        ,Main            ,1490.5  ,0,2109.4,,,,,
Observed WS=CHERRYRV        ,Main            ,191.4   ,0,2088.7,,,,,
DSS Import GetInterval= 0
DSS Import GetPeak= 0
DSS Import FillOption= 0

--- CHERRYRV.f03 (steady flow) ---

Flow Title=Floodway
Program Version=5.07
Number of Profiles= 2
Profile Names=P100yr,Floodway
River Rch & RM=CHERRYRV,Main            ,23057
   24148   24148
River Rch & RM=CHERRYRV,Main            ,11640
   28085   28085
River Rch & RM=CHERRYRV,Main            ,2287
   35300   35300
Boundary for River Rch & Prof#=CHERRYRV,Main            , 1
Up Type= 0
Dn Type= 1
Dn Known WS=2097.5
Boundary for River Rch & Prof#=CHERRYRV,Main            , 2
Up Type= 0
Dn Type= 1
Dn Known WS=2097.5
DSS Import GetInterval= 0
DSS Import GetPeak= 0
DSS Import FillOption= 0

--- CHERRYRV.f05 (steady flow) ---

Flow Title=June16
Program Version=4.10
Number of Profiles= 1
Profile Names=June16
River Rch & RM=CHERRYRV,Main            ,23057
   21000
River Rch & RM=CHERRYRV,Main            ,19881
   23447
River Rch & RM=CHERRYRV,Main            ,11640
   28900
River Rch & RM=CHERRYRV,Main            ,2287
   36000
Boundary for River Rch & Prof#=CHERRYRV,Main            , 1
Up Type= 0
Dn Type= 3
Dn Slope=0.00336
Observed WS=CHERRYRV        ,Main            ,22454   ,0,2218.6
Observed WS=CHERRYRV        ,Main            ,22158   ,0,2206.1
Observed WS=CHERRYRV        ,Main            ,21627   ,0,2206.1
Observed WS=CHERRYRV        ,Main            ,21335   ,0,2204
Observed WS=CHERRYRV        ,Main            ,21104   ,0,2201.8
Observed WS=CHERRYRV        ,Main            ,20415   ,0,2197.9
Observed WS=CHERRYRV        ,Main            ,20113   ,0,2197.4
Observed WS=CHERRYRV        ,Main            ,19251   ,0,2193.4
Observed WS=CHERRYRV        ,Main            ,19022   ,0,2190.8
Observed WS=CHERRYRV        ,Main            ,18616   ,0,2189.6
Observed WS=CHERRYRV        ,Main            ,18198   ,0,2186.6
Observed WS=CHERRYRV        ,Main            ,16757   ,0,2185.1
Observed WS=CHERRYRV        ,Main            ,15707   ,0,2180
Observed WS=CHERRYRV        ,Main            ,14867   ,0,2178
Observed WS=CHERRYRV        ,Main            ,14057   ,0,2176.8
Observed WS=CHERRYRV        ,Main            ,13878   ,0,2175.8
Observed WS=CHERRYRV        ,Main            ,13385   ,0,2174.6
Observed WS=CHERRYRV        ,Main            ,12625   ,0,2171.6
Observed WS=CHERRYRV        ,Main            ,11640   ,0,2165.8
Observed WS=CHERRYRV        ,Main            ,10359   ,0,2161.2
Observed WS=CHERRYRV        ,Main            ,8500    ,0,2151.5
Observed WS=CHERRYRV        ,Main            ,5177    ,0,2129.3
Observed WS=CHERRYRV        ,Main            ,4579    ,0,2125.8
Observed WS=CHERRYRV        ,Main            ,3830    ,0,2121.7
Observed WS=CHERRYRV        ,Main            ,3377    ,-250,2121.4
Observed WS=CHERRYRV        ,Main            ,2951    ,0,2117.8
Observed WS=CHERRYRV        ,Main            ,1865    ,-40,2113.5
Observed WS=CHERRYRV        ,Main            ,1490    ,0,2109.4
Observed WS=CHERRYRV        ,Main            ,54      ,100,2088.7
DSS Import GetInterval= 0
DSS Import GetPeak= 0
DSS Import FillOption= 0

--- CHERRYRV.f06 (steady flow) ---

Flow Title=Gage-Based Flows_17C
Program Version=5.03
Number of Profiles= 6
Profile Names=P100yr_17C,P10yr_17C,P25yr_17C,P50yr_17C,P100yrPLUS_17C,P500yr_17C
River Rch & RM=CHERRYRV,Main            ,23053.8
   24148   11558   15825   19715   41324   37937
River Rch & RM=CHERRYRV,Main            ,11636.4
   26082   12511   17112   21294   44635   40887
River Rch & RM=CHERRYRV,Main            ,2282.6
   35300   17080   23260   28820   60410   54860
Boundary for River Rch & Prof#=CHERRYRV,Main            , 1
Up Type= 0
Dn Type= 1
Dn Known WS=2098.63
Boundary for River Rch & Prof#=CHERRYRV,Main            , 2
Up Type= 0
Dn Type= 1
Dn Known WS=2095.12
Boundary for River Rch & Prof#=CHERRYRV,Main            , 3
Up Type= 0
Dn Type= 1
Dn Known WS=2096.83
Boundary for River Rch & Prof#=CHERRYRV,Main            , 4
Up Type= 0
Dn Type= 1
Dn Known WS=2097.69
Boundary for River Rch & Prof#=CHERRYRV,Main            , 5
Up Type= 0
Dn Type= 1
Dn Known WS=2102.13
Boundary for River Rch & Prof#=CHERRYRV,Main            , 6
Up Type= 0
Dn Type= 1
Dn Known WS=2101.91
Observed WS=CHERRYRV        ,Main            ,23053.8 ,0,2218.6,,,,,
Observed WS=CHERRYRV        ,Main            ,22450   ,0,2206.1,,,,,
Observed WS=CHERRYRV        ,Main            ,22154.2 ,0,2206.1,,,,,
Observed WS=CHERRYRV        ,Main            ,21624   ,0,2204,,,,,
Observed WS=CHERRYRV        ,Main            ,21117   ,0,2201.8,,,,,
Observed WS=CHERRYRV        ,Main            ,20411.4 ,0,2197.9,,,,,
Observed WS=CHERRYRV        ,Main            ,20109.9 ,0,2197.4,,,,,
Observed WS=CHERRYRV        ,Main            ,19018.1 ,0,2190.8,,,,,
Observed WS=CHERRYRV        ,Main            ,18195   ,0,2186.6,,,,,
Observed WS=CHERRYRV        ,Main            ,15703.3 ,0,2180,,,,,
Observed WS=CHERRYRV        ,Main            ,14863.1 ,0,2178,,,,,
Observed WS=CHERRYRV        ,Main            ,13381.7 ,0,2174.6,,,,,
Observed WS=CHERRYRV        ,Main            ,12621.1 ,0,2171.6,,,,,
Observed WS=CHERRYRV        ,Main            ,3826.5  ,0,2121.7,,,,,
Observed WS=CHERRYRV        ,Main            ,1490.5  ,0,2109.4,,,,,
Observed WS=CHERRYRV        ,Main            ,191.4   ,0,2088.7,,,,,
DSS Import GetInterval= 0
DSS Import GetPeak= 0
DSS Import FillOption= 0

--- CHERRYRV.g03 (geometry) ---

Geom Title=1mDEM
Program Version=5.03

River Reach=CHERRYRV        ,Main
Reach XY= 30
     2105861.325      446650.219     2105496.742      446489.628
     2104823.999      446433.205     2103851.777      445556.469
     2103001.082      445317.753     2098847.046      445175.791
     2097163.409      444875.045     2096798.825      444697.094
     2096410.485      444168.539     2095902.288      443784.292
      2095466.36      443737.892     2094706.811      444258.726
     2094168.617      445135.462      2093591.36      445118.101
     2093358.721       444828.17     2093018.443      444789.976
      2092747.61       444921.92     2092646.623      445160.192
     2092421.221      445317.753      2092185.11      445404.559
     2091883.027      445248.309     2091357.323      445496.688
     2090899.497      445935.226      2089292.49      445765.795
     2088824.867      446039.976     2088146.916      446751.905
     2088100.909      446938.413     2088291.013      448456.642
     2088629.554      449185.809     2088616.534      449373.309

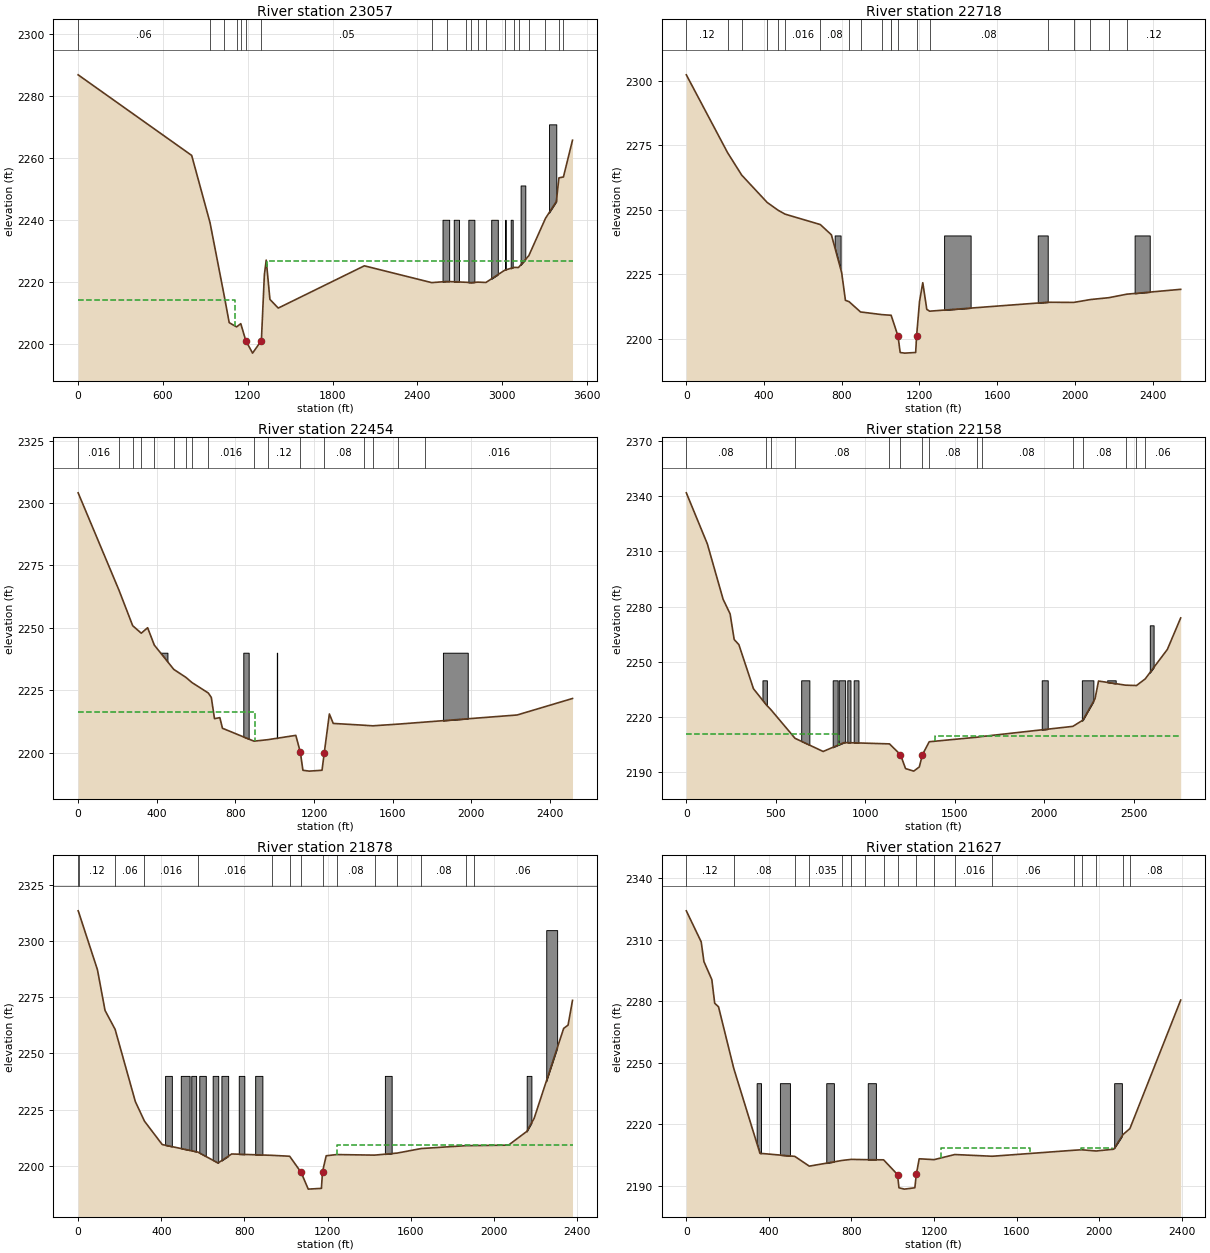
Type RM Length L Ch R = 1 ,23057   ,350.1,339.5,323.6
Node Name=W
XS GIS Cut Line= 4
     2105650.995      445425.238     2105871.015      446309.986
     2105167.749      447817.753      2104310.11      448158.031
#Sta/Elev= 30
       0 2286.85   803.5  2260.8     933 2239.12  1034.8 2215.17  1068.9 2206.75
  1121.3 2205.38  1150.8 2206.43  1186.8 2200.89  1234.3  2196.9 1296.63 2200.95
  1317.8 2222.22  1330.9 2226.97  1357.1 2214.26    1416 2211.46  2025.2 2225.12
  2501.7 2219.69  2609.92220.059  2746.32219.798  2777.8  2219.7    2829 2219.85
  2885.42219.737  3019.7 2223.74  3084.3  2224.6  3116.1 2224.58  3189.1 2228.42
  3306.8 2240.45  3383.6 2245.89  3402.1 2253.55  3433.92253.843  3498.1 2265.71
#Mann= 20 ,-1 , 0
       0     .06       0     933    .016       0  1034.8     .08       0
  1121.3     .05       0  1150.8     .05       0  1186.8     .04       0
 1296.63     .05       0  2501.7    .016       0  2609.9     .08       0
  2746.3     .09       0  2777.8     .08       0    2829    .016       0
  2885.4     .08       0  3019.7    .016       0  3084.3     .09       0
  3116.1     .08       0  3189.1    .016       0  3306.8     .06       0
  3402.1    .016       0  3433.9     .06       0
#XS Ineff= 2 , 0
         1112.56 2214.07 1335.34         2226.73
Permanent Ineff=
       F       F
#Block Obstruct= 13 ,-1
   26.47   83.23    2240   95.45  117.37    2240  265.04  311.37    2240
  585.42  628.22    2240  754.11  796.43    2240  2578.4 2625.39    2240
 2657.82  2694.9    2240  2761.2 2803.62    2240 2922.92 2969.58    2240
 3022.24 3024.95    2240 3060.73 3074.79    2240 3130.94 3164.052251.089
    3332  3383.32270.843
Bank Sta=1186.8,1296.63
XS Rating Curve= 0 ,0
Exp/Cntr=0.3,0.1

Type RM Length L Ch R = 1 ,22718   ,269.3,263.9,256.4
Node Name=V
XS GIS Cut Line= 4
2105490.04160168445348.4522944652105462.39760681446228.452797757
2105406.11286538446571.3201732432104850.78730933447765.710853325
#Sta/Elev= 30
       0  2302.3  212.472272.099  285.362263.381  416.092252.811  473.242249.734
     5092248.249  689.752244.224   746.9 2240.24   799.8 2225.53   819.1 2214.84
  837.87 2214.31  896.822210.321 1005.982209.295 1053.472209.034  1054.4 2209.05
    1090 2200.88  1100.9  2194.6 1123.69 2194.35  1180.7  2194.6 1185.34 2200.85
  1200.6 2214.42  1217.3 2221.66    1238 2211.33  1252.7 2210.62 1861.232214.077
 1994.982214.026 2080.542215.133 2174.142215.844 2268.242217.221  2545.1  2219.1
#Mann= 20 ,-1 , 0
       0     .12       0  212.47    .016       0  285.36     .06       0
  416.09    .016       0  473.24     .08       0     509    .016       0
  689.75     .08       0  837.87    .016       0  896.82     .08       0
 1005.98    .016       0 1053.47     .08       0  1054.4     .06       0
    1090    .045       0 1185.34     .05       0  1252.7     .08       0
 1861.23     .06       0 1994.98     .06       0 2080.54     .08       0
 2174.14    .016       0 2268.24     .12       0
#Block Obstruct= 8 ,-1
     3.3   20.29    2240   93.17  128.89    2240  485.43  515.46    2240
  684.65   689.1    2240  763.65  794.06    2240 1327.09 1463.57    2240
 1809.15 1860.48    2240 2307.82 2385.68    2240
Bank Sta=1090,1185.34
XS Rating Curve= 0 ,0
Exp/Cntr(USF)=0,0
Exp/Cntr=0.8,0.6

Type RM Length L Ch R = 1 ,22454   ,270.6,296.1,320.3
XS GIS Cut Line= 5
2105413.23082517 445322.686285272105254.36805003446117.000160982
2105161.54934994446359.7567611992105156.19442494446638.212861449
2104692.10092452447707.412887407
#Sta/Elev= 30
       0 2304.05  207.79 2265.03  277.522250.819  321.042247.818   353.4 2250.01
  387.462243.037   486.4 2233.32  548.622230.089  578.742228.048   661.82223.866
   677.2 2222.08   693.5 2213.58   720.6 2213.99     734 2209.73  893.982204.565
   963.82205.147    1107 2206.89    1130 2200.14  1143.1 2192.91 1174.78 2192.56
 1240.23 2192.91 1251.87    2200  1277.6 2215.46  1297.3 2211.67 1453.862210.945
 1498.18 2210.71  1628.22211.394 1763.632212.215  2232.4 2215.05    2514 2221.66
#Mann= 17 ,-1 , 0
       0    .016       0  207.79     .06       0  277.52     .08       0
  321.04    .016       0  387.46     .08       0   486.4    .016       0
  548.62     .08       0  578.74     .06       0   661.8    .016       0
  893.98     .06       0   963.8     .12       0    1130    .035       0
 1251.87     .08       0 1453.86    .016       0 1498.18     .08       0
  1628.2    .016       0 1763.63    .016       0
#XS Ineff= 2 , 0
          898.65 2216.11
Permanent Ineff=
       F       F
#Block Obstruct= 7 ,-1
  275.71  305.07    2240  331.97   334.5    2240  397.35  409.35    2240
  418.82  454.09    2240  839.88  867.17    2240 1010.34 1012.12    2240
 1855.02 1981.22    2240
Bank Sta=1130,1251.87
XS Rating Curve= 0 ,0
Exp/Cntr(USF)=0,0
Exp/Cntr=0.3,0.1

Type RM Length L Ch R = 1 ,22158   ,260.6,280.2,297.1
XS GIS Cut Line= 4
     2105181.172      445262.105     2105194.223      445705.827
     2104370.024      447587.096     2104137.122      447715.624
#Sta/Elev= 30
       0 2341.83   117.5 2314.09   205.6 2284.04   244.8 2276.09   267.6 2262.16
   293.8 2259.38   375.4 2235.42   446.6 2226.74   472.8 2224.06   607.7 2208.51
   764.9 2201.36   882.9 2206.22  1135.8 2205.47  1197.3  2199.6  1225.5 2192.07
  1271.4 2190.68 1302.43 2192.94 1320.08 2199.62  1357.8 2206.63  1626.5 2209.12
  1651.6 2209.47  2160.8 2214.99    2217 2218.37  2284.9 2230.01  2304.5 2239.61
  2455.8 2237.36  2516.6 2237.17  2565.5 2240.77  2689.2 2256.78  2763.8 2273.89
#Mann= 15 ,-1 , 0
       0     .08       0   446.6    .016       0   472.8     .06       0
   607.7     .08       0  1135.8     .08       0  1197.3    .035       0
 1320.08     .06       0  1357.8     .08       0  1626.5    .016       0
  1651.6     .08       0  2160.8    .016       0    2217     .08       0
  2455.8     .09       0  2516.6    .016       0  2565.5     .06       0
#XS Ineff= 2 , 0
          854.73 2210.65 1391.89         2209.65
Permanent Ineff=
       F       F
#Block Obstruct= 12 ,-1
  225.16   265.7    2240  319.66  351.79    2240  425.61  450.23    2240
  642.13  687.84    2240  818.36   845.9    2240  852.11  887.95    2240
  899.88  917.67    2240  935.56  962.26    2240 1986.94 2020.33    2240
 2211.21  2275.7    2240 2352.58 2400.34    2240    2591 2612.292269.867
Bank Sta=1197.3,1320.08
XS Rating Curve= 0 ,0
Exp/Cntr=0.3,0.1

Type RM Length L Ch R = 1 ,21878   ,250.3,250.3,245.2
XS GIS Cut Line= 4
2105159.55625028445366.3875662422105100.79164118445785.085406123
2104329.50614666446642.0692889212103869.18337533447298.274090607
#Sta/Elev= 30
       0 2313.61    1.922313.209      93  2287.3   129.4 2269.18  177.912260.737
   275.2 2228.52  319.122219.792   404.4 2209.38   575.5 2206.03   672.7 2201.16
   738.2 2205.18   932.4 2204.57 1017.192204.167  1072.3 2196.96 1106.56  2189.5
  1169.9 2189.84  1175.1 2197.23  1192.8 2204.37  1243.12204.911 1425.752204.665
 1534.422205.577  1650.12207.605 1865.942208.886 1902.032208.912  2069.6 2209.12
  2157.8 2215.26    2193 2221.12  2334.8 2261.18    2356 2262.65  2377.3 2273.68
#Mann= 15 ,-1 , 0
       0    .016       0    1.92     .12       0  177.91     .06       0
  319.12    .016       0   575.5    .016       0   932.4     .06       0
 1017.19     .05       0  1072.3    .045       0  1175.1     .06       0
  1243.1     .08       0 1425.75     .08       0 1534.42    .016       0
  1650.1     .08       0 1865.94    .016       0 1902.03     .06       0
#XS Ineff= 2 , 0
                         1247.21          2209.3
Permanent Ineff=
       F       F
#Block Obstruct= 12 ,-1
  170.79  207.81    2240  418.17  450.58    2240  493.59  535.91    2240
  544.05  567.31    2240  582.56  613.84    2240  646.98  673.74    2240
  688.98  721.45    2240  772.41  799.13    2240  851.33  886.03    2240
 1475.06  1507.6    2240 2157.04 2179.62    2240 2251.06 2303.43    2305
Bank Sta=1072.3,1175.1
XS Rating Curve= 0 ,0
Exp/Cntr(USF)=0,0
Exp/Cntr=0.3,0.1

Type RM Length L Ch R = 1 ,21627   ,293.5,292.5,282.4
XS GIS Cut Line= 4
2105154.66160473445328.6959033192104507.25117165446069.282031482
2104411.18767599446180.8465022412103699.60659826447225.448952755
#Sta/Elev= 30
       0  2324.1    72.1 2308.95    85.2 2299.36   123.5 2290.56   137.5 2279.01
     156 2277.27  229.732247.231   356.7 2205.78   525.3  2204.3  595.652199.522
   755.4 2202.32  799.612202.835  863.492202.698   955.62202.607  1023.3 2195.39
    1030 2188.97  1056.3 2188.31  1107.1 2188.97    1114 2195.45    1128 2203.11
  1200.4  2202.7  1300.3 2205.19  1482.1 2204.35 1875.872207.266    19152207.509
  1985.1 2206.92  2070.1 2207.78 2115.562214.943 2148.742217.857  2394.8 2280.55
#Mann= 18 ,-1 , 0
       0     .12       0  229.73     .08       0   525.3     .08       0
  595.65    .035       0   755.4     .08       0  799.61     .12       0
  863.49     .08       0   955.6     .06       0  1023.3    .045       0
    1114     .06       0  1200.4     .08       0  1300.3    .016       0
  1482.1     .06       0 1875.87    .016       0    1915     .06       0
  1985.1     .08       0 2115.56    .016       0 2148.74     .08       0
#XS Ineff= 2 ,-1
 1235.92 1666.67  2208.5  1910.9  2060.1  2208.5
Permanent Ineff=
       F       F
#Block Obstruct= 6 ,-1
   88.22  124.06    2240  340.68  361.64    2240  453.29  501.93    2240
  677.89  714.77    2240  878.92  918.28    2240 2072.59 2109.84    2240
Bank Sta=1023.3,1114
XS Rating Curve= 0 ,0
Exp/Cntr(USF)=0,0
Exp/Cntr=0.3,0.1

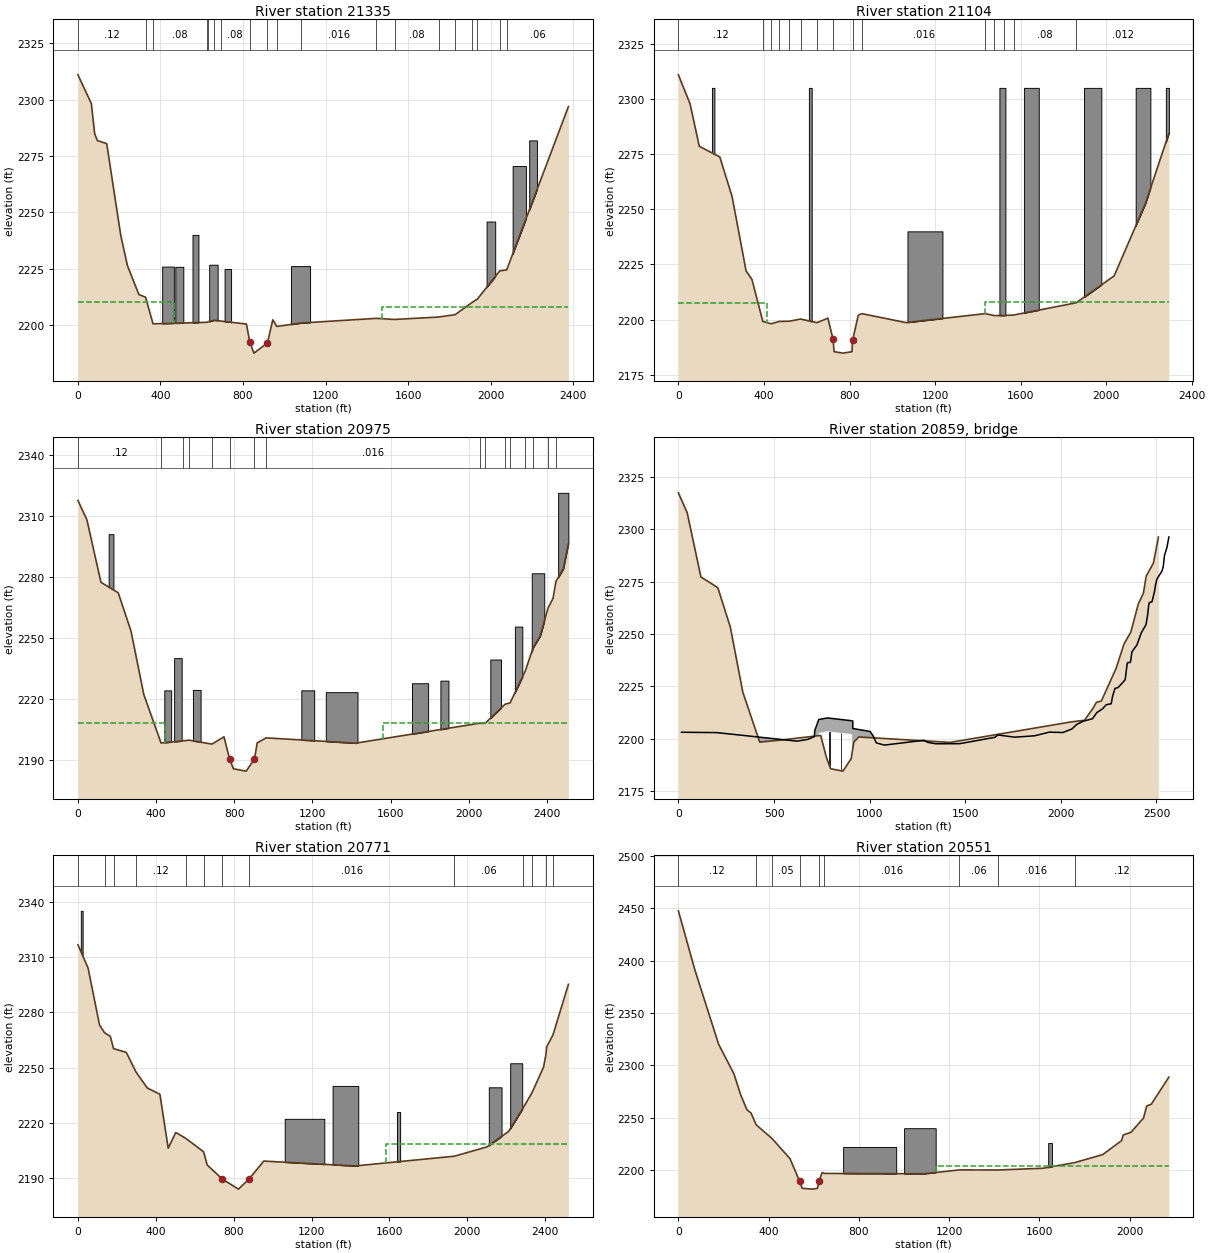
Type RM Length L Ch R = 1 ,21335   ,221.5,230.7,247.3
XS GIS Cut Line= 3
     2104580.943      445158.031     2104601.777      445442.753
     2103369.667      447132.679
#Sta/Elev= 30
       0 2311.06    64.9 2298.34    81.1 2284.89    94.1 2281.88   139.5  2280.5
   207.6 2239.74   240.1 2226.29   295.3 2213.52   327.5 2212.35     364 2200.52
   623.1 2201.18   629.8 2201.35   661.2 2202.14     692 2201.75   816.5 2200.42
   832.9 2192.45  852.85 2187.51   918.2 2192.01   944.4  2202.3   963.7 2199.37
    1082 2200.88  1446.4 2202.95  1534.3 2202.46  1747.6 2203.53  1828.1  2204.6
  1911.4 2210.09  1935.8 2211.52  2044.4 2224.06  2077.7 2224.43  2376.9 2296.97
#Mann= 19 ,-1 , 0
       0     .12       0   327.5     .08       0     364     .08       0
   623.1    .016       0   629.8     .08       0   661.2    .016       0
     692     .08       0   832.9     .03       0   918.2     .06       0
   963.7     .08       0    1082    .016       0  1446.4    .016       0
  1534.3     .08       0  1747.6    .016       0  1828.1     .06       0
  1911.4    .016       0  1935.8     .06       0  2044.4    .016       0
  2077.7     .06       0
#XS Ineff= 2 , 0
          463.95 2210.24 1474.59            2208
Permanent Ineff=
       F       F
#Block Obstruct= 9 ,-1
  408.29  464.682225.932  471.96  510.592225.827  555.19  583.84    2240
  636.14  676.942226.755  710.65  742.132224.835 1032.74 1124.962226.137
 1980.37 2022.172245.932 2106.56  2170.92270.556 2186.91 2224.322281.955
Bank Sta=832.9,918.2
XS Rating Curve= 0 ,0
Exp/Cntr=0.3,0.1

Type RM Length L Ch R = 1 ,21104   ,106.8,129,245.1
XS GIS Cut Line= 4
2104538.13867732445152.0319595292104246.08106756445632.047436959
2104006.07332884 445822.896964132103310.46857072447066.149902493
#Sta/Elev= 30
       02310.905  54.4732297.795   97.56 2278.56  193.572273.704 251.1752255.731
 316.4622222.063 343.9032218.196  394.822199.186  434.432198.135  471.572199.185
  518.972199.284  571.122200.289 648.2772198.638 698.9572200.675   723.32191.023
 727.918 2185.48  768.77 2184.84 811.751 2185.48  814.33 2190.65 841.0932202.021
 857.5762202.7291063.7262198.675 1435.492202.742 1475.252201.852 1521.672201.902
 1566.732202.086 1859.852207.6452037.4222219.8442183.2522252.5382293.1422284.359
#Mann= 15 ,-1 , 0
       0     .12       0  394.82     .06       0  434.43     .07       0
  471.57     .08       0  518.97    .016       0  571.12     .08       0
 648.277     .06       0   723.3     .03       0  814.33     .06       0
 857.576    .016       0 1435.49    .016       0 1475.25     .08       0
 1521.67    .016       0 1566.73     .08       0 1859.85    .012       0
#XS Ineff= 2 , 0
          413.71 2207.75 1435.29            2208
Permanent Ineff=
       F       F
#Block Obstruct= 8 ,-1
   156.8  168.46    2305  610.03  623.22    2305 1070.97 1234.49    2240
 1500.83 1528.99    2305 1615.44 1684.81    2305 1896.54 1977.29    2305
 2137.92 2206.73    2305 2279.05 2293.15    2305
Bank Sta=723.3,814.33
XS Rating Curve= 0 ,0
Exp/Cntr(USF)=0,0
Exp/Cntr=0.5,0.3

Type RM Length L Ch R = 1 ,20975   ,200.2,203.6,150.3
BEGIN DESCRIPTION:
Merged DS Survey CHE042BU
END DESCRIPTION:
XS GIS Cut Line= 5
     2104526.082      445130.774     2104234.416      445638.587
     2104079.207      445646.747     2103773.652       445730.08
     2103257.428      447087.847
#Sta/Elev= 30
       0 2317.54    45.8 2308.08   117.8 2277.29   206.1 2272.17   271.5 2253.35
     337 2222.16   425.3 2198.27   535.2 2199.28   569.2 2199.64     686 2197.72
   747.6  2201.3  776.02 2190.33   796.2 2185.55     861 2184.42   903.6 2190.39
   917.4  2198.3   963.1 2200.78  1421.7 2198.17  2055.9 2207.99  2083.8 2207.89
  2185.7  2217.3    2212 2217.99  2289.2 2233.61  2330.5 2245.26  2366.1 2250.93
  2405.4 2264.48  2431.6 2269.44  2446.5 2277.73  2484.1  2283.9  2510.3 2296.36
#Mann= 16 ,-1 , 0
       0     .12       0   425.3     .06       0   535.2    .016       0
   569.2     .08       0     686     .06       0  776.02     .04       0
   903.6     .06       0   963.1    .016       0  2055.9    .016       0
  2083.8     .08       0  2185.7    .016       0    2212     .08       0
  2289.2    .016       0  2330.5     .08       0  2405.4    .016       0
  2446.5     .08       0
#XS Ineff= 2 , 0
          443.26 2208.26 1561.57            2208
Permanent Ineff=
       F       F
#Block Obstruct= 12 ,-1
  157.02   181.72300.969  441.97  477.142224.139  492.29  530.98    2240
  588.55  627.81 2224.38 1143.27  1209.2 2224.16 1268.58 1430.842223.259
  1709.7 1792.292227.652 1855.15 1896.242228.925 2110.54 2165.152239.321
 2236.39 2274.392255.518 2322.55 2386.662281.741 2457.78 2510.052321.313
Bank Sta=776.02,903.6
XS Rating Curve= 0 ,0
Exp/Cntr=0.5,0.3

Type RM Length L Ch R = 3 ,20859   ,,,
BEGIN DESCRIPTION:
Dyer Avenue. Merged DS Survey CHE040RP
END DESCRIPTION:
Bridge Culvert--1,0,-1,-1, 0
Deck Dist Width WeirC Skew NumUp NumDn MinLoCord MaxHiCord MaxSubmerge Is_Ogee
100,37,2.6,0, 60, 60, , , , 0, ,,,
    16.4   200.3   619.4   676.2   709.6     712     713     734  779.24     909
     912   912.1  1002.5  1018.9  1035.2  1077.8  1284.2  1303.8  1346.4  1470.9
  1654.3  1670.7  1759.2    1864  1939.3  2011.4  2057.2  2083.4  2119.5  2165.3
  2188.3  2217.8  2237.4  2263.6  2270.2  2283.3  2299.6  2335.7  2338.9  2345.5
  2348.8  2361.9  2365.2  2371.7  2397.9  2420.8  2443.8    2447  2453.6  2460.1
  2463.4  2476.5  2489.6  2496.2  2502.7  2528.9  2535.5    2542  2555.1    2565
 2203.01 2202.85 2198.77 2199.59 2200.87    2202  2203.8  2209.1 2209.87  2208.5
  2208.3  2204.8 2203.39 2201.19 2197.91 2196.88 2199.17 2198.18 2197.52 2197.55
 2200.57 2201.72 2200.66 2201.34 2203.06  2202.9 2204.55 2206.79 2208.39 2209.46
 2212.43  2214.2 2216.19 2216.65 2220.09    2224 2224.41 2228.03 2229.78 2234.86
 2236.33  2236.4 2237.06 2241.47 2244.76 2250.61  2254.2 2255.26 2258.99 2264.16
 2265.09 2265.37 2270.21 2273.93 2276.32  2280.1 2282.28 2287.55 2291.45 2296.44
                                                          2202.7 2203.47  2202.1
                                                                                
                                                                                
                                                                                
                                                                                
                                                                                
       0    42.5    52.3    65.4    81.8   127.6   170.1   189.7     265   291.1
   317.3   343.4   356.5   372.9   389.2     422   451.4   474.3   614.5     713
   713.1  713.92     735  759.24     911     915   915.1   982.5  1015.2  1057.8
  1264.2  1326.4  1450.9  1650.7  1739.2  1991.4  2099.5  2145.3  2217.4  2243.6
  2250.2  2263.3  2279.6  2315.7  2328.8  2341.9  2345.2  2351.7  2377.9  2400.8
  2423.8  2433.6  2440.1  2456.5  2482.7  2508.9  2515.5    2522  2535.1    2545
 2315.85 2309.31 2306.35 2298.01  2294.2 2271.61 2267.95 2263.52 2258.77 2254.67
 2252.58 2240.89 2238.46 2232.86 2229.22 2210.66 2199.63 2198.26 2199.44  2203.8
  2207.3 2208.99  2209.5 2209.87  2208.5    2208  2204.5 2203.39 2197.91 2196.88
 2199.17 2197.52 2197.55 2201.72 2200.66  2202.9 2208.39 2209.46 2216.19 2216.65
 2220.09    2224 2224.41 2228.03 2236.33  2236.4 2237.06 2241.47 2244.76 2250.61
  2254.2 2258.99 2264.16 2265.37 2276.32  2280.1 2282.28 2287.55 2291.45 2296.44
                                                                                
                                                                                
                  2203.1 2203.47  2202.1
                                                                                
                                                                                
                                                                                
Pier Skew, UpSta & Num, DnSta & Num=  ,791.58, 2 ,793.57, 2 , 0 , 0 , 0 ,0,0
       3       3
    2180    2205
       3       3
    2180    2205
Pier Skew, UpSta & Num, DnSta & Num=  ,851.33, 2 ,855.17, 2 , 0 , 0 , 0 ,0,0
       3       3
    2180    2205
       3       3
    2180    2205
BR Coef=-1 , 1 , 0 ,, 0 ,,,0.8,0,1.33,0,
WSPro=,,,, 1 ,,,, 0 ,,,, 0 ,,,,-1 ,-1 ,-1 , 0 , 0 , 0 , 0 , 0
BR U #Sta/Elev= 30
       0 2317.54    45.8 2308.08   117.8 2277.29   206.1 2272.17   271.5 2253.35
     337 2222.16   425.3 2198.27   535.2 2199.28   569.2 2199.64   744.3 2201.48
     774    2191   796.2 2185.55     861 2184.42   903.6 2190.39   917.4  2198.3
   943.5 2200.75  1421.7 2198.17  2055.9 2207.99  2123.4 2208.75  2169.3 2214.61
  2185.7  2217.3    2212 2217.99  2289.2 2233.61  2330.5 2245.26  2366.1 2250.93
  2405.4 2264.48  2431.6 2269.44  2446.5 2277.73  2484.1  2283.9  2510.3 2296.36
BR U #Mann= 15
       0     .12   425.3     .06   535.2    .016   569.2    .016     774    .035
   903.6    .016   943.5    .016  2055.9    .016  2169.3     .08  2185.7    .016
    2212     .08  2289.2    .016  2330.5     .08  2405.4    .016  2446.5     .08
BR U Banks=774,903.6
BR D #Sta/Elev= 30
       0 2316.71    52.2 2304.02     111 2273.05   136.6 2268.91   166.5 2266.91
   182.9 2260.26   248.2 2258.23   298.7 2247.49   355.9 2238.91   421.2 2235.41
   463.7 2206.15   502.4 2214.69   553.8 2211.52   645.6 2204.19   663.8 2197.05
   742.2 2189.31   824.8  2183.9   879.3 2189.42   954.4 2199.15  1422.6 2196.49
  1979.2 2202.59  2100.3 2206.83    2218 2217.86  2267.3 2221.97  2288.6 2228.36
  2391.8 2250.23  2403.1 2256.66  2408.1 2261.31    2440  2267.7  2519.4  2295.2
BR D #Mann= 12
       0     .12   136.6    .016   182.9     .06   298.7     .12   553.8     .06
   645.6    .016   742.2    .035   879.3    .016    2218     .06  2288.6    .016
  2403.1    .016    2440     .12
BR D Banks=742.2,879.3
BC Design=,, 0 ,, 0 ,,0,,,,
BC HTab HWMax=0
BC HTab TWMax=0
BC HTab MaxFlow=0
BC Use User HTab Curves=0
BC User HTab FreeFlow(D)= 0

Type RM Length L Ch R = 1 ,20771   ,271.9,220.3,60.8
BEGIN DESCRIPTION:
Merged US Survey CHE038BD
END DESCRIPTION:
XS GIS Cut Line= 5
     2104400.388      445088.587     2104164.103      445487.545
     2103971.568      445507.858     2103666.013      445591.191
     2103116.788      447035.758
#Sta/Elev= 30
       0 2316.71    52.2 2304.02     111 2273.05   136.6 2268.91   166.5 2266.91
   182.9 2260.26   248.2 2258.23   298.7 2247.49   355.9 2238.91   421.2 2235.41
   463.7 2206.15   502.4 2214.69   553.8 2211.52   645.6 2204.19   663.8 2197.05
   742.2 2189.31   824.8  2183.9   879.3 2189.42   954.4 2199.15  1422.6 2196.49
  1933.4 2201.79  2100.3 2206.83  2211.7 2215.21  2288.6 2228.36  2332.2 2236.26
  2391.8 2250.23  2403.1 2256.66  2408.1 2261.31    2440  2267.7  2519.4  2295.2
#Mann= 13 ,-1 , 0
       0     .12       0   136.6    .016       0   182.9     .06       0
   298.7     .12       0   553.8     .06       0   645.6     .08       0
   742.2     .04       0   879.3    .016       0  1933.4     .06       0
  2288.6    .016       0  2332.2     .06       0  2403.1    .016       0
    2440     .12       0
#XS Ineff= 2 , 0
          503.52 2214.56 1580.99         2208.26
Permanent Ineff=
       F       F
#Block Obstruct= 6 ,-1
   14.74   24.082335.153 1062.17 1265.522222.117 1307.96 1439.87    2240
  1638.5 1655.042225.807 2110.39 2175.952239.236 2220.25 2282.132252.298
Bank Sta=742.2,879.3
XS Rating Curve= 0 ,0
Exp/Cntr=0.5,0.3

Type RM Length L Ch R = 1 ,20551   ,137.9,136.3,127.2
Node Name=U
XS GIS Cut Line= 4
2103769.58947653444948.8132977652103648.94647482445386.799847424
2103583.37962607445633.3311987282103108.67564111447018.103044355
#Sta/Elev= 30
       0 2447.53    72.6 2391.43   178.1 2320.25   246.2 2291.87   276.8 2271.37
     304 2257.56   321.1 2254.69   344.9 2243.21   415.5 2230.07   494.5 2210.94
  537.48 2189.19   548.8 2182.64   594.9 2181.84   616.4 2182.64   622.42189.347
   637.1 2197.64   647.3 2196.84  1087.3  2196.5  1244.9 2200.19  1415.9 2200.11
  1617.1 2201.78  1756.3 2207.17  1880.3 2214.82  1963.9 2228.18  1970.8 2233.51
  2005.5 2236.12  2061.1 2249.72  2074.9 2261.17  2095.7 2263.02  2173.3 2288.79
#Mann= 9 ,-1 , 0
       0     .12       0   344.9    .016       0   415.5     .05       0
  537.48    .045       0   622.4     .08       0   647.3    .016       0
  1244.9     .06       0  1415.9    .016       0  1756.3     .12       0
#XS Ineff= 2 , 0
                          1142.1          2204.2
Permanent Ineff=
       F       F
#Block Obstruct= 6 ,-1
   14.74   24.082335.153     730     9652222.117    1000    1140    2240
  1638.5 1655.042225.807 2110.39 2175.952239.236 2220.25 2282.132252.298
Bank Sta=537.48,622.4
XS Rating Curve= 0 ,0
Exp/Cntr(USF)=0,0
Exp/Cntr=0.5,0.3