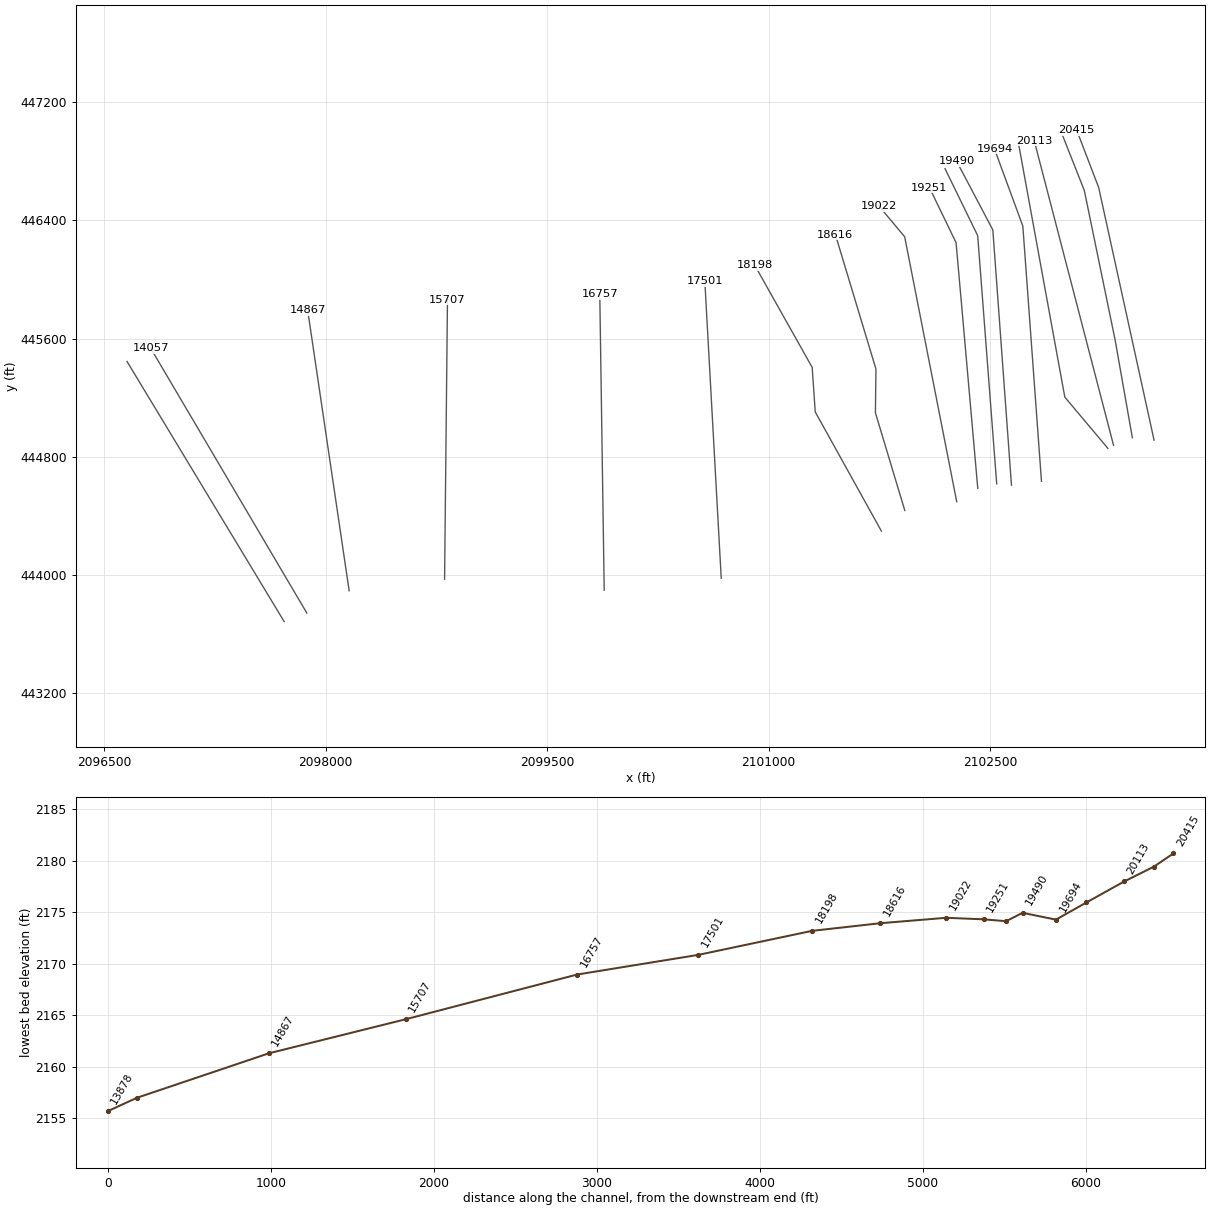
HEC-RAS study CHERRYRV.prj: CHERRYRV

--- CHERRYRV.g03 (geometry) --- (continued)

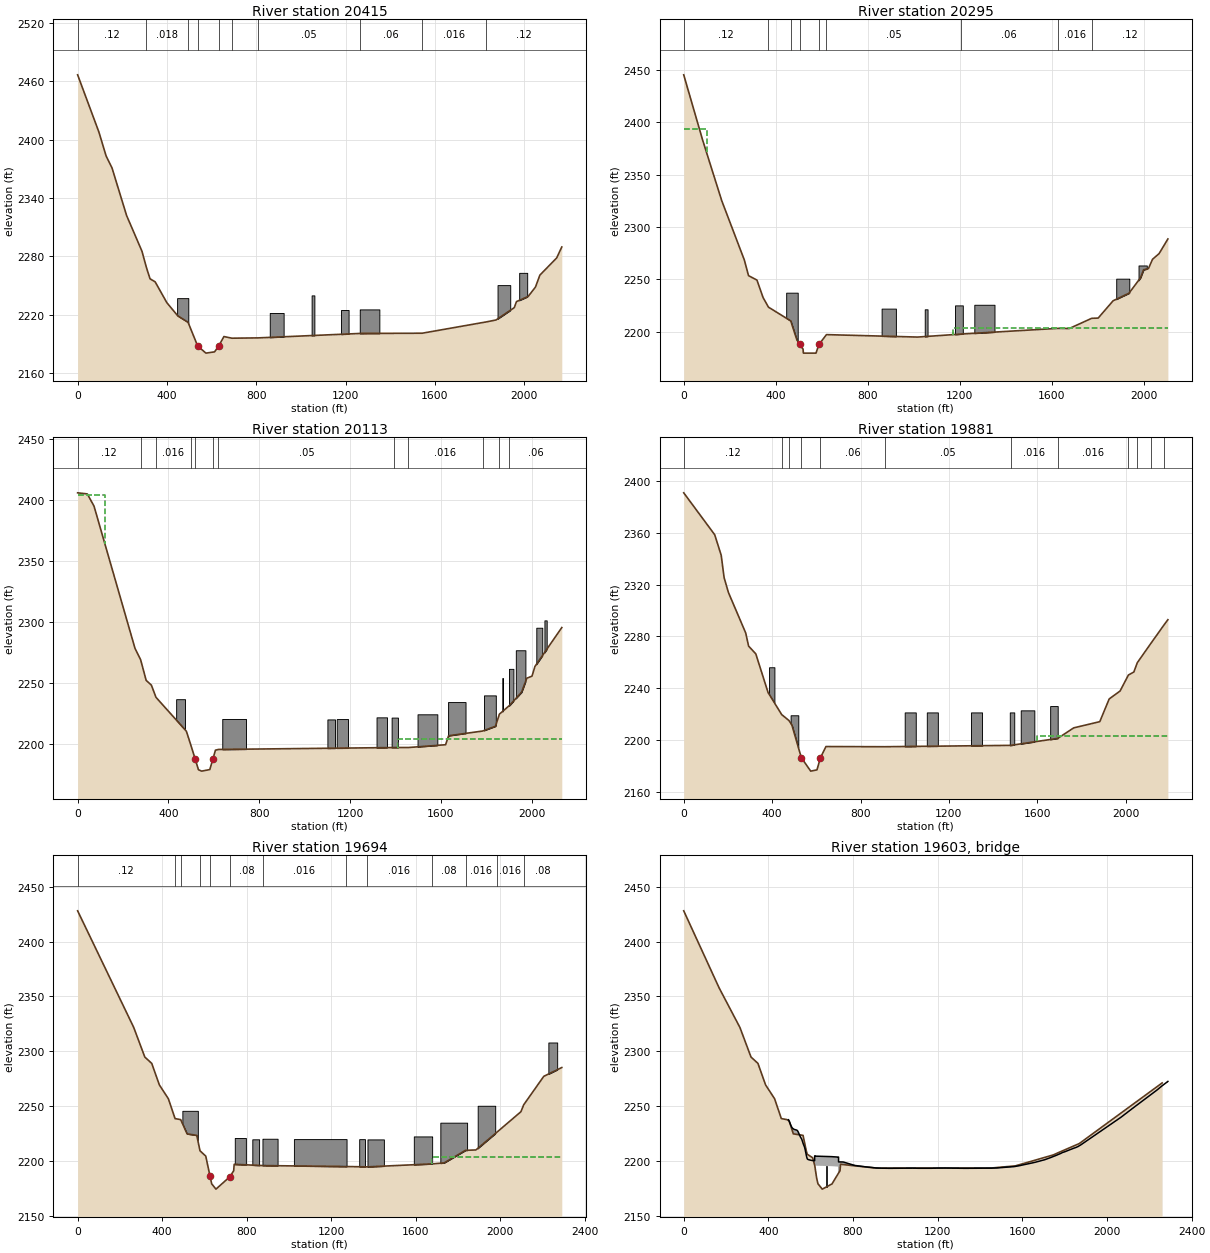
Type RM Length L Ch R = 1 ,20415   ,119.5,120.2,115.4
XS GIS Cut Line= 3
     2103608.721      444911.503     2103233.721      446623.309
     2103085.086      447011.535
#Sta/Elev= 30
       0 2466.59      95 2407.99   127.7 2383.18     154 2370.94   219.5 2321.94
   288.2 2285.34   308.2 2268.55   324.3 2257.04   347.2 2253.91   399.6  2232.5
   448.8 2218.88   494.6 2212.36  537.57 2187.97   574.6 2180.69  613.05 2181.98
   632.2 2188.15   655.1 2197.72   691.1 2196.03     809 2196.35  1264.4  2200.9
  1542.8 2201.14  1827.7 2212.66  1873.5 2214.74  1955.3  2227.4  1965.2 2233.62
  2017.5 2238.91  2050.3  2248.6  2069.9  2260.8  2145.2  2278.5  2168.1 2289.73
#Mann= 10 ,-1 , 0
       0     .12       0   308.2    .018       0   494.6     .04       0
  537.57     .03       0   632.2    .045       0   691.1     .06       0
     809     .05       0  1264.4     .06       0  1542.8    .016       0
  1827.7     .12       0
#Block Obstruct= 7 ,-1
  445.47  495.582237.176  860.35  922.452221.946 1047.86 1060.12    2240
 1179.57 1213.362225.022  1263.4 1351.13 2225.61 1880.33  1937.22250.557
 1977.28 2013.192263.166
Bank Sta=537.57,632.2
XS Rating Curve= 0 ,0
Exp/Cntr=0.3,0.1

Type RM Length L Ch R = 1 ,20295   ,178.4,181.3,191.8
XS GIS Cut Line= 4
  2103461.766235444928.3302142152103344.92611053445591.132374872
2103136.73825238446602.3305430542102990.15700531446974.094575473
#Sta/Elev= 30
       0 2445.32    81.9 2383.22   165.2  2325.1   263.8 2268.22   281.8 2253.43
   318.4 2249.17   345.1 2232.47   368.4 2223.34   465.3 2210.18   491.7 2192.15
     504  2187.7   518.7 2183.32  520.35  2179.4     575  2179.4     588  2187.7
   620.6 2197.08  1016.6 2194.75  1204.2 2197.58  1626.2 2203.06  1676.5 2202.93
  1773.7 2212.66  1801.9 2212.89  1866.9 2229.44  1935.9 2236.64  1985.8 2251.34
  1999.4 2259.07  2020.5 2260.19  2038.2 2269.07  2066.7 2274.48    2105 2288.49
#Mann= 9 ,-1 , 0
       0     .12       0   368.4    .016       0   465.3    .045       0
     504     .03       0     588    .045       0   620.6     .05       0
  1204.2     .06       0  1626.2    .016       0  1773.7     .12       0
#XS Ineff= 2 , 0
          103.01 2393.15 1168.76         2203.14
Permanent Ineff=
       F       F
#Block Obstruct= 7 ,-1
  445.47  495.582237.176  860.35  922.452221.946 1047.86 1060.122221.256
 1179.57 1213.362225.022  1263.4 1351.13 2225.61 1880.33  1937.22250.557
 1977.28 2013.192263.166
Bank Sta=504,588
XS Rating Curve= 0 ,0
Exp/Cntr(USF)=0,0
Exp/Cntr=0.3,0.1

Type RM Length L Ch R = 1 ,20113   ,234.4,231.9,225.1
XS GIS Cut Line= 2
     2103334.416      444876.781      2102797.45      446940.354
#Sta/Elev= 30
       0 2406.08    42.6 2405.19    72.2 2395.19   252.6 2278.64   277.5 2269.27
   301.8 2252.38   324.8 2248.48   345.2 2238.44     479 2210.65   498.6 2199.34
   518.3 2187.57  532.18 2179.12  546.18 2177.97  582.12 2179.24   595.5 2187.75
   606.9 2195.12     620 2195.74  1395.52197.303  1456.5 2197.31  1620.5  2199.6
  1633.7 2206.98  1783.6 2210.83  1840.3 2214.75  1857.5 2224.67  1901.7 2231.76
  1955.2 2242.64  1978.1 2254.12  2001.1 2255.82  2014.2 2263.83  2132.3 2295.64
#Mann= 12 ,-1 , 0
       0     .12       0   277.5     .08       0   345.2    .016       0
   498.6     .05       0   518.3    .035       0   595.5     .05       0
     620     .05       0  1395.5     .06       0  1456.5    .016       0
  1783.6     .06       0  1857.5    .016       0  1901.7     .06       0
#XS Ineff= 2 , 0
          119.73 2404.02 1412.49         2204.65
Permanent Ineff=
       F       F
#Block Obstruct= 14 ,-1
  433.91  473.092236.923  636.98  741.432220.737 1100.04 1133.492220.343
 1141.08 1190.972220.644 1316.44 1362.462222.053 1382.83 1410.642221.847
 1496.96 1584.182224.546 1631.53 1708.372234.564 1789.64 1841.712240.046
 1870.73  1872.62254.292 1900.01 1919.152261.798 1929.83 1972.072277.033
 2020.04 2046.332295.506 2055.83 2065.742301.535
Bank Sta=518.3,595.5
XS Rating Curve= 0 ,0
Exp/Cntr=0.3,0.1

Type RM Length L Ch R = 1 ,19881   ,190.8,187.1,184.4
XS GIS Cut Line= 3
     2103296.221      444855.948     2103004.554       445203.17
     2102692.663      446912.455
#Sta/Elev= 30
       0 2390.95   140.3 2358.56   169.6 2342.75   182.7 2325.47   202.3 2313.96
   280.6 2282.63   293.6 2272.53   326.2 2266.52   381.7 2236.66   443.3 2219.63
   476.4 2215.01   489.5  2211.5   532.2 2186.33   574.6 2175.93  602.93 2176.89
  618.62 2186.21   643.6 2194.92   909.2 2194.78  1479.6 2195.84  1692.7 2201.23
  1764.8 2209.35  1882.8 2214.15  1925.4 2231.72  1974.6 2237.82  2012.3 2250.19
  2036.9  2252.5  2052.6 2259.71  2112.6 2274.28  2174.6 2289.18    2191 2292.92
#Mann= 12 ,-1 , 0
       0     .12       0   443.3    .016       0   476.4     .06       0
   532.2     .03       0  618.62     .06       0   909.2     .05       0
  1479.6    .016       0  1692.7    .016       0  2012.3    .016       0
  2052.6     .06       0  2112.6    .016       0  2174.6     .06       0
#XS Ineff= 2 , 0
                         1600.63         2202.76
Permanent Ineff=
       F       F
#Block Obstruct= 10 ,-1
   386.2  410.382256.178  483.69  518.452219.079    1000    10502221.289
    1100    11502221.289    1300    13502221.289 1475.54 1495.682221.289
 1525.09 1586.612222.886 1658.26 1692.382226.202 1968.25 1995.432221.289
 2061.75 2106.422221.289
Bank Sta=532.2,618.62
XS Rating Curve= 0 ,0
Exp/Cntr=0.5,0.3

Type RM Length L Ch R = 1 ,19694   ,204.6,204.5,204.5
BEGIN DESCRIPTION:
Merged DS Survey CHE032BU
END DESCRIPTION:
XS GIS Cut Line= 3
     2102846.568      444632.858     2102720.383      446361.938
     2102528.229      446884.723
#Sta/Elev= 30
       0 2428.13   265.5 2321.74   317.9 2294.75   350.7 2288.95   386.7 2269.35
   429.3 2256.72   461.1 2238.61   487.7 2237.65   517.8 2224.67   563.7 2223.31
     579 2209.24   606.3 2204.37  626.63 2185.84   634.2 2179.12   654.5 2174.26
   721.3 2185.75   738.4 2191.05   740.7  2196.9     875 2195.76  1268.3 2194.88
  1369.9 2194.56  1674.7 2197.26  1733.7 2198.16  1835.2 2209.65  1884.4    2210
  1982.7 2226.02  2097.4 2244.89  2110.4 2251.17  2205.5 2277.16  2290.7 2285.19
#Mann= 13 ,-1 , 0
       0     .12       0   461.1    .016       0   487.7     .06       0
     579     .05       0  626.63    .035       0   721.3     .08       0
     875    .016       0  1268.3     .05       0  1369.9    .016       0
  1674.7     .08       0  1835.2    .016       0  1982.7    .016       0
  2110.4     .08       0
#XS Ineff= 2 , 0
                         1677.62         2203.47
Permanent Ineff=
       F       F
#Block Obstruct= 11 ,-1
  495.59  568.762245.696  743.55  796.052220.903  826.46  858.552219.705
  874.47  946.012220.224 1023.32 1272.392219.898 1332.17 1359.542219.847
 1371.34 1448.942219.617 1590.57 1677.322222.337 1716.07 1842.682234.877
 1892.83 1975.712250.301 2227.17 2268.872308.022
Bank Sta=626.63,721.3
XS Rating Curve= 0 ,0
Exp/Cntr=0.5,0.3

Type RM Length L Ch R = 3 ,19603   ,,,
BEGIN DESCRIPTION:
Oakford Ave. Merged DS Survey CHE030RP
END DESCRIPTION:
Bridge Culvert--1,0,-1,-1, 0
Deck Dist Width WeirC Skew NumUp NumDn MinLoCord MaxHiCord MaxSubmerge Is_Ogee
68,31,2.6,0, 60, 60, , , , 0, ,,,
   495.1   508.2   511.5   514.8   521.3   534.5   537.7     541   550.8   557.4
   560.7     564   570.5   573.8   580.4   583.6   586.9   596.8   603.3  618.54
  618.55  621.11  621.75  697.55  728.78  731.47  731.48  753.53  804.09  804.19
   849.2     905   931.2   973.8    1082  1111.5  1167.3  1196.8  1236.1  1327.9
  1455.8  1478.8  1560.7  1583.7  1659.1    1705  1731.2  1760.8  1780.4  1790.2
    1800  1842.5  1852.4  1862.2  1875.2    2065  2127.1  2235.1    2258  2287.4
 2237.53 2231.58 2230.41 2229.71  2228.8 2228.06  2227.5 2226.35 2222.04 2219.84
 2218.04 2215.94 2212.75 2210.23 2203.97 2201.88 2201.31 2200.78 2200.48  2200.2
  2204.6  2204.6 2204.36  2203.9  2203.5  2203.5  2199.1 2199.02 2196.09 2195.97
 2194.81 2193.65 2193.36 2193.23 2193.42 2193.26 2193.26 2193.45 2193.49 2193.23
  2193.4 2193.57  2194.8 2195.55 2198.68 2201.06 2202.89 2205.15 2206.76 2207.72
 2208.33 2211.57 2212.21 2213.08 2214.53 2239.73 2248.89 2264.54  2268.2 2272.52
                                                                                
                                                                                
          2195.9 2195.66  2195.2  2194.8
                                                                                
                                                                                
                                                                                
      -8    11.7    28.1    41.2    57.6    70.7   113.3   126.4   146.1   169.1
     192   205.1     215   228.1   270.7   280.5   290.4   306.8     310   319.9
   323.2   326.4   359.2   369.1   378.9   388.7     392   408.4   424.8   431.4
   444.5     451     474   483.8   500.2   503.5   510.1   529.7   549.4   562.5
   565.8   572.4   575.6   595.3  625.72  625.73  627.11  736.25  738.77  738.78
  796.19     897   965.8  1470.8  1575.7    1697  1844.4  1867.2    2057  2279.4
 2460.05 2452.88 2445.47 2441.44 2433.89 2428.66    2409  2401.1 2392.02 2379.51
 2369.55 2364.57 2361.56 2355.54 2339.08 2336.25 2330.48 2318.72 2315.32 2302.65
 2299.71 2298.26 2294.34 2287.72 2282.77 2276.68 2275.16 2269.74 2262.61 2260.74
 2254.17  2252.1 2242.21 2238.94 2231.58 2230.41 2229.19  2227.5 2219.84 2212.75
 2210.23 2203.97 2201.88 2200.48  2199.9  2204.3  2204.3  2203.5  2203.5  2199.1
 2195.97 2193.65 2193.23 2193.57 2195.55 2201.06 2212.21 2214.53 2239.73 2272.52
                                                                                
                                                                                
                                                                                
                                                                                
                                                  2195.6  2194.8
                                                                                
Pier Skew, UpSta & Num, DnSta & Num=  ,675.32, 2 ,682.19, 2 , 0 , 0 , 0 ,0,0
       3       3
    2170    2200
       3       3
    2170    2200
BR Coef=-1 , 1 , 0 ,, 0 ,,,0.8,0,1.33,0,
WSPro=,,,, 1 ,,,, 0 ,,,, 0 ,,,,-1 ,-1 ,-1 , 0 , 0 , 0 , 0 , 0
BR U #Sta/Elev= 30
       0 2428.13   167.1  2357.9   265.5 2321.74   317.9 2294.75   350.7 2288.95
   386.7 2269.35   429.3 2256.72   461.1 2238.61   487.7 2237.65   498.2  2236.5
   517.8 2224.67   563.7 2223.31     579 2209.24   583.4  2206.1   609.2 2202.86
   619.4 2195.46   627.8 2184.48   634.2 2179.12   654.5 2174.26   700.6    2179
  717.45 2184.48   738.4 2191.05   740.7  2196.9   910.9 2193.44  1457.3 2193.58
  1567.2 2195.48  1746.8 2205.52  1766.8 2207.28  1868.9 2215.84  2260.2 2271.12
BR U #Mann= 9
       0     .12   461.1    .016   487.7     .08     579    .016   609.2     .06
   627.8     .03  717.45     .06  1746.8    .016  1766.8     .08
BR U Banks=627.8,717.45
BR D #Sta/Elev= 30
       0 2503.07   108.2  2461.2   157.3 2437.27   196.6 2412.57   226.1  2390.3
   321.2 2330.91   342.8 2312.54   360.5 2297.89   376.9    2294   399.8 2275.39
   455.5 2245.01   488.3 2223.75   534.2 2211.15   553.9 2208.75   576.8 2198.01
   599.7 2193.89   616.1 2191.83   629.2 2184.63   651.4  2176.6   666.8 2174.92
  731.77 2184.67   739.3  2187.7   740.7  2196.9   910.9 2193.44  1300.1 2193.33
  1540.8 2194.75  1707.5 2202.16  1858.1 2214.49  2182.8 2259.53  2260.2 2271.12
BR D #Mann= 9
       0     .12   342.8    .016   376.9     .12   576.8    .016   599.7     .08
   629.2     .03  731.77     .08  1300.1    .016  2182.8     .08
BC Design=,, 0 ,, 0 ,,0,,,,
BC HTab HWMax=0
BC HTab TWMax=0
BC HTab MaxFlow=0
BC Use User HTab Curves=0
BC User HTab FreeFlow(D)= 0

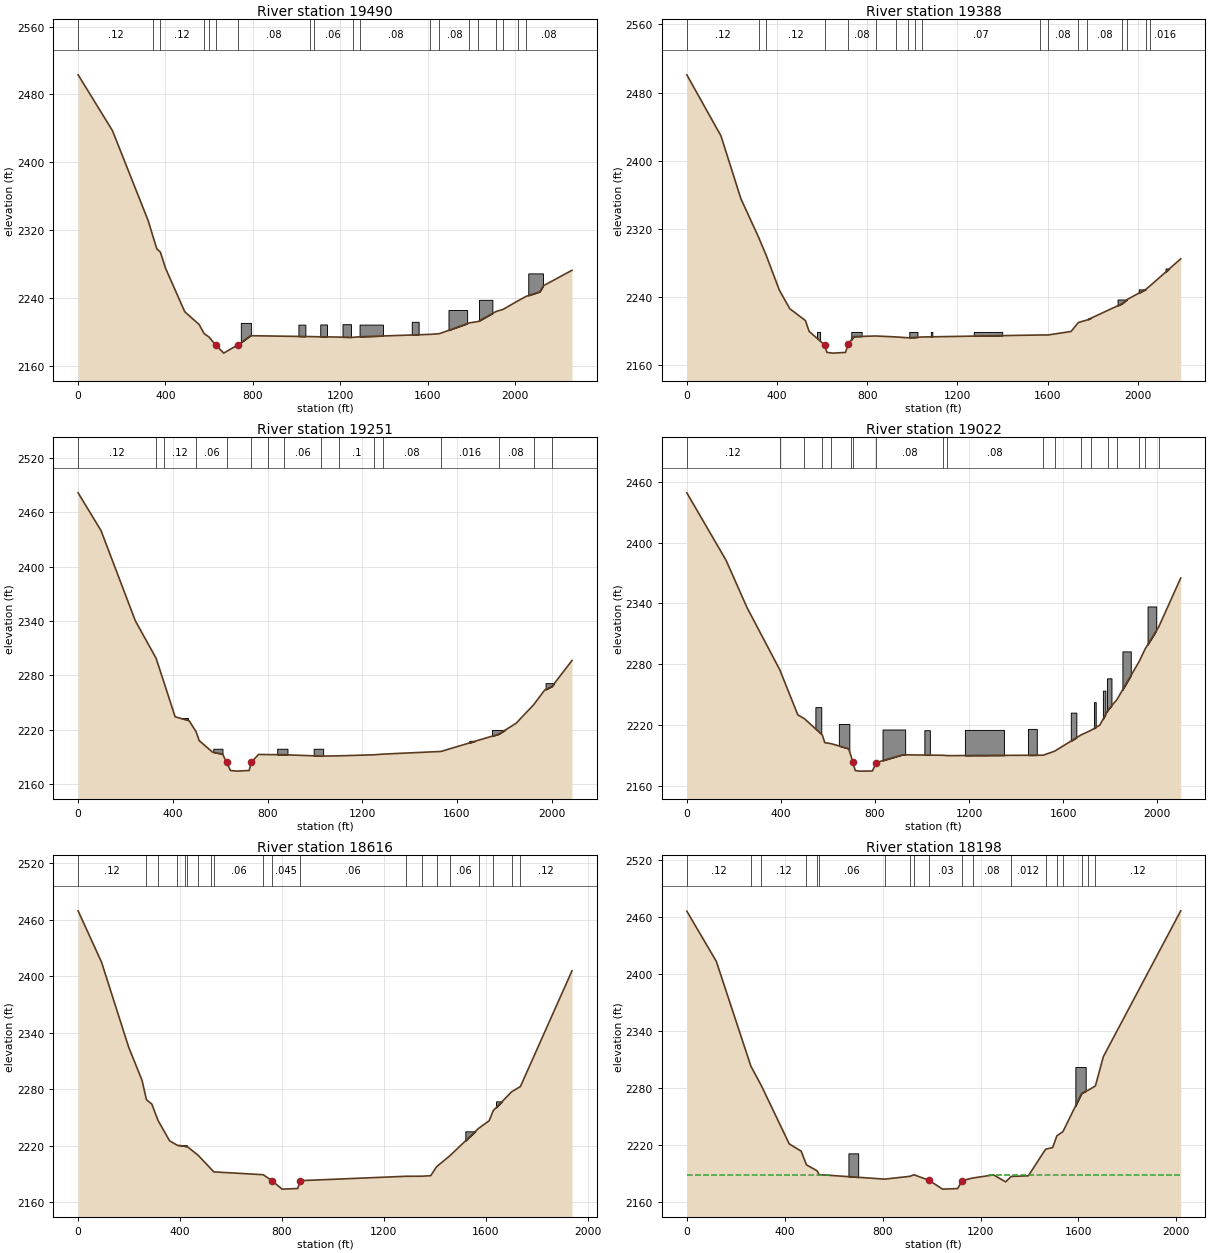
Type RM Length L Ch R = 1 ,19490   ,101.3,101.4,101.6
BEGIN DESCRIPTION:
Merged US Survey CHE028BD
END DESCRIPTION:
XS GIS Cut Line= 3
     2102643.443      444606.816     2102517.258      446335.896
     2102271.125      446802.966
#Sta/Elev= 30
       0 2503.07   157.3 2437.27   321.2 2330.91   342.8 2312.54   360.5 2297.89
   376.9    2294   399.8 2275.39   488.3 2223.75   553.9 2208.75   576.8 2198.01
   599.7 2193.89   629.2 2184.63   666.8 2174.92  731.77 2184.67   789.8 2195.45
  1061.8 2194.44  1079.5 2194.32  1257.2 2193.55  1291.8 2194.23  1613.4 2197.06
  1654.5 2197.87  1791.6 2210.57  1831.4 2212.17  1913.6 2223.98  1946.8 2226.56
  2012.4 2236.35  2052.2 2241.93  2114.1 2247.19  2130.5 2254.36  2261.6 2272.61
#Mann= 19 ,-1 , 0
       0     .12       0   342.8    .016       0   376.9     .12       0
   576.8    .016       0   599.7    .045       0   629.2    .035       0
  731.77     .08       0  1061.8    .016       0  1079.5     .06       0
  1257.2    .016       0  1291.8     .08       0  1613.4    .016       0
  1654.5     .08       0  1791.6    .016       0  1831.4     .08       0
  1913.6    .016       0  1946.8     .08       0  2012.4    .016       0
  2052.2     .08       0
#Block Obstruct= 9 ,-1
  745.16   791.12210.553 1008.83 1040.642208.536 1108.82 1139.522208.719
 1210.74 1249.442209.032 1288.91 1395.862208.539  1527.9 1559.342211.848
 1696.05 1781.392225.738 1835.73 1896.92 2237.72 2061.37 2128.512268.929
Bank Sta=629.2,731.77
XS Rating Curve= 0 ,0
Exp/Cntr=0.5,0.3

Type RM Length L Ch R = 1 ,19388   ,137.4,137.8,138.5
XS GIS Cut Line= 3
2102543.49337396444615.7553354042102414.74976465446297.108442098
2102193.77192777446750.593394304
#Sta/Elev= 30
       0 2500.84   151.4 2429.16   239.7 2355.47  318.362310.065  352.012288.947
   410.8 2247.79   456.9 2226.22     526 2212.39   542.5 2199.63   610.92183.858
   621.4 2174.94  647.88 2174.11   703.7 2174.94     716 2184.69  740.53 2193.51
   839.1 2194.22   927.7 2193.14  981.942192.128 1011.562192.458 1043.212193.054
  1565.8 2195.41 1602.592195.438  1704.4 2199.56 1736.772210.055 1776.282213.094
  1931.2 2232.17 1954.022237.202  2034.8 2248.76 2055.04  2253.2  2190.7 2284.84
#Mann= 18 ,-1 , 0
       0     .12       0  318.36    .016       0  352.01     .12       0
   610.9    .045       0     716     .08       0   839.1    .016       0
   927.7     .06       0  981.94     .08       0 1011.56    .016       0
 1043.21     .07       0  1565.8    .016       0 1602.59     .08       0
 1736.77    .016       0 1776.28     .08       0  1931.2     .08       0
 1954.02    .016       0  2034.8     .06       0 2055.04    .016       0
#Block Obstruct= 9 ,-1
  577.55  591.15    2199  729.41  775.38    2199  986.66 1022.98    2199
 1082.31 1088.92    2199 1272.65 1398.89    2199 1779.38 1820.942215.058
 1910.45 1952.592237.074 2004.49 2039.672248.917 2123.31 2139.692273.509
Bank Sta=610.9,716
XS Rating Curve= 0 ,0
Exp/Cntr(USF)=0,0
Exp/Cntr=0.3,0.1

Type RM Length L Ch R = 1 ,19251   ,224.4,229.1,238.5
XS GIS Cut Line= 4
2102415.37804449444584.5969246072102306.25318678 445822.92683176
2102268.29671453446249.9371445712102088.00347134446622.385028524
#Sta/Elev= 30
       0 2481.45    96.7 2439.82   241.6 2340.24  329.192298.953  363.292271.752
   409.6 2234.31   469.1 2229.83   498.5 2217.68   511.4 2207.96   567.7 2195.27
   610.5 2192.93   627.5 2183.83   643.4 2174.98  670.24 2174.29   722.5 2174.98
  730.98 2183.96     762 2192.72     802 2192.54  869.882192.378  1027.12190.885
  1101.2 2191.17 1251.362192.332 1287.622193.067 1532.212196.003  1775.6 2214.99
  1849.6 2227.11  1923.7 2247.59  1969.8 2263.59  2001.5  2267.8  2085.6 2296.39
#Mann= 16 ,-1 , 0
       0     .12       0  329.19    .016       0  363.29     .12       0
   498.5     .06       0   627.5    .045       0  730.98    .016       0
     802     .12       0  869.88     .06       0  1027.1    .016       0
  1101.2      .1       0 1251.36    .016       0 1287.62     .08       0
 1532.21    .016       0  1775.6     .08       0  1923.7    .016       0
  2001.5     .12       0
#Block Obstruct= 7 ,-1
  428.93  464.142232.802  570.95  609.64    2199  840.59     884    2199
  994.82 1034.75    2199 1651.85 1675.512207.743 1747.99 1804.072219.763
 1974.07 2009.872271.386
Bank Sta=627.5,730.98
XS Rating Curve= 0 ,0
Exp/Cntr(USF)=0,0
Exp/Cntr=0.3,0.1

Type RM Length L Ch R = 1 ,19022   ,414.7,405.9,387.8
XS GIS Cut Line= 3
     2102272.795      444494.931     2101920.428      446289.392
     2101746.046      446498.028
#Sta/Elev= 30
       0 2449.05   167.1 2382.39   255.6 2335.98   395.4 2274.43   471.9 2230.02
     500 2226.19   576.5 2210.03   586.6 2202.55   614.5 2201.51   688.2 2196.48
   700.1 2188.15   704.6  2183.5  716.64    2175  735.58 2174.44  789.07 2174.56
   806.2 2182.91   917.6 2190.55  1090.8 2190.08  1107.7 2189.73    1516 2190.16
    1564 2194.08  1676.5 2210.16  1719.4 2214.74  1756.6 2219.86  1791.1 2234.68
  1829.4 2245.06  1924.2 2282.75  1949.3 2295.03  2007.2 2316.84  2100.6 2364.96
#Mann= 19 ,-1 , 0
       0     .12       0   395.4    .016       0     500     .08       0
   576.5    .016       0   614.5     .08       0   700.1    .035       0
   704.6    .045       0   806.2     .08       0  1090.8    .016       0
  1107.7     .08       0    1516    .016       0    1564     .08       0
  1676.5    .016       0  1719.4     .08       0  1791.1    .016       0
  1829.4     .06       0  1924.2    .016       0  1949.3     .06       0
  2007.2     .12       0
#Block Obstruct= 12 ,-1
  546.79  571.73 2237.59  646.54  691.112220.976  832.34  928.572215.518
 1010.24 1033.562214.813  1182.7 1348.66 2215.11 1450.96 1488.362216.124
 1633.06 1656.672232.163 1731.47 1738.972242.499 1769.61 1780.132253.876
 1786.75 1806.012265.993 1852.63 1888.172292.579 1959.54 1996.262336.929
Bank Sta=704.6,806.2
XS Rating Curve= 0 ,0
Exp/Cntr=0.3,0.1

Type RM Length L Ch R = 1 ,18616   ,413.3,417.4,423.9
XS GIS Cut Line= 4
2101921.30139028444435.2026130722101722.43631886445096.880941617
2101726.05204743445393.3706844622101451.25667601446304.534284425
#Sta/Elev= 30
       0 2469.47    92.1  2414.9   198.3 2324.83     251 2289.48  268.362268.814
   289.5 2264.21  313.742246.906   359.3 2225.18  388.562220.622  421.022219.374
   428.72219.061  470.672210.038  523.632194.844  532.362192.244  726.98  2189.2
   761.4 2182.86   800.9 2173.91   862.4 2174.57   871.8 2182.89  1285.8 2187.55
 1350.772187.645  1384.4 2188.17 1407.922197.866 1458.372209.056  1572.8  2238.5
    1614 2246.58 1629.762257.245  1701.8 2277.21 1736.542282.856  1939.1 2405.76
#Mann= 20 ,-1 , 0
       0     .12       0  268.36    .016       0  313.74     .12       0
  388.56     .06       0  421.02     .12       0   428.7     .06       0
  470.67    .016       0  523.63     .12       0  532.36     .06       0
  726.98     .12       0   761.4    .045       0   871.8     .06       0
  1285.8     .06       0 1350.77     .12       0 1407.92    .016       0
 1458.37     .06       0  1572.8    .016       0 1629.76     .08       0
  1701.8    .016       0 1736.54     .12       0
#Block Obstruct= 3 ,-1
  387.63  426.732220.616 1520.38 1560.192235.298 1640.77 1677.142267.109
Bank Sta=761.4,871.8
XS Rating Curve= 0 ,0
Exp/Cntr(USF)=0,0
Exp/Cntr=0.3,0.1

Type RM Length L Ch R = 1 ,18198   ,697.5,697,695.5
XS GIS Cut Line= 4
     2101763.023      444295.417     2101315.106      445102.709
     2101294.273      445404.7922100906.38614239446094.955405287
#Sta/Elev= 30
       02466.104 120.1882413.418   261.82302.674  304.562282.231 418.3492220.858
 467.1252213.163  488.792198.776  532.332192.457  540.242188.457 808.5572183.719
   911.8 2186.68 927.9552188.322 990.4392182.334 1044.66 2173.17 1106.26 2173.77
1125.2722182.2181168.0252184.8641253.1582188.1711302.6622180.8551325.2422186.576
1395.3112187.202  1465.7 2215.261494.5992217.016  1511.82229.362 1536.542233.777
 1613.442274.221 1640.41 2277.49 1669.262281.9931701.591 2312.772017.7242466.498
#Mann= 19 ,-1 , 0
       0     .12       0   261.8    .016       0  304.56     .12       0
  488.79    .016       0  532.33     .12       0  540.24     .06       0
 808.557     .12       0   911.8    .016       0 927.955     .06       0
 990.439     .03       01125.272     .08       01168.025     .08       0
1325.242    .012       0  1465.7    .016       0  1511.8     .08       0
 1536.54     .06       0 1613.44     .08       0 1640.41    .016       0
 1669.26     .12       0
#XS Ineff= 2 , 0
          590.91 2187.96 1235.63         2187.87
Permanent Ineff=
       F       F
#Block Obstruct= 2 ,-1
  660.16  700.032210.876 1587.26 1629.452301.829
Bank Sta=990.439,1125.272
XS Rating Curve= 0 ,0
Exp/Cntr(USF)=0,0
Exp/Cntr=0.3,0.1

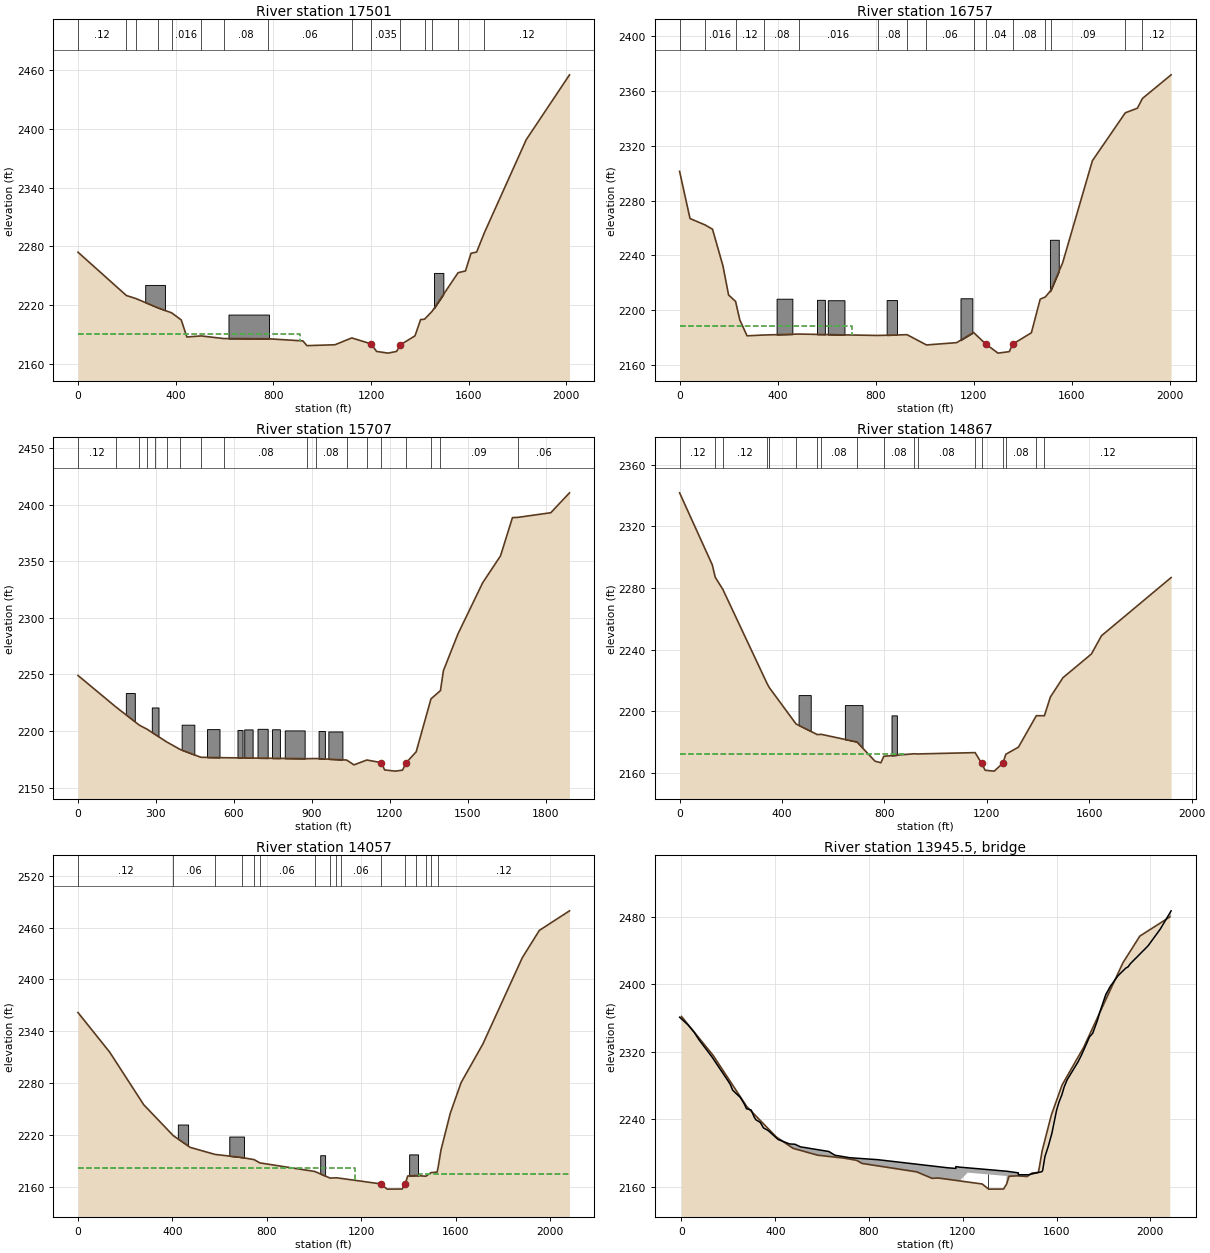
Type RM Length L Ch R = 1 ,17501   ,745.5,743.7,740.9
XS GIS Cut Line= 2
     2100678.705      443976.618     2100567.775      445986.415
#Sta/Elev= 30
       0 2274.02   198.3 2229.71   236.5 2226.69   328.5 2217.02   383.2 2212.07
   422.9 2204.77   445.8 2187.33   504.1 2188.43   597.3 2185.73     777 2185.54
   921.2 2183.32   937.6 2178.49  1052.3  2179.4  1121.2 2186.38  1199.8 2180.34
  1222.8 2172.58  1269.8 2170.84  1304.8 2172.58  1320.1 2179.31  1380.2 2188.51
  1403.1 2205.16  1419.1 2205.49  1450.2 2213.59  1556.7 2253.07  1586.7 2254.81
  1609.6  2272.9  1632.6 2274.16  1663.8 2293.65  1835.8 2389.07  2012.9 2455.32
#Mann= 15 ,-1 , 0
       0     .12       0   198.3     .06       0   236.5     .08       0
   328.5     .12       0   383.2    .016       0   504.1     .06       0
   597.3     .08       0     777     .06       0  1121.2     .08       0
  1199.8    .035       0  1320.1     .05       0  1419.1    .016       0
  1450.2     .09       0  1556.7    .016       0  1663.8     .12       0
#XS Ineff= 2 , 0
          908.58 2190.82
Permanent Ineff=
       F       F
#Block Obstruct= 3 ,-1
  275.21  356.052240.564  616.26  782.172210.259 1457.85 1496.212252.835
Bank Sta=1199.8,1320.1
XS Rating Curve= 0 ,0
Exp/Cntr=0.3,0.1

Type RM Length L Ch R = 1 ,16757   ,1054.8,1050.7,1048.7
XS GIS Cut Line= 2
     2099886.499      443895.531     2099856.516      445901.586
#Sta/Elev= 30
       0 2301.25    42.6  2266.9   104.4 2262.21   134.4 2259.14     177 2232.46
     200 2211.24   228.5 2206.58   245.9 2193.04   275.4 2181.53   344.2 2182.12
   488.4  2182.8   808.1 2181.79   928.6 2182.35  1007.8 2174.89    1131 2176.56
  1199.8    2184    1249 2175.66  1299.7 2168.93  1345.7 2170.01  1360.5 2175.55
  1435.9 2183.73  1471.9  2208.2  1492.7 2209.79  1515.3 2214.58  1563.7 2234.76
    1685    2309  1819.4 2343.89  1868.6 2347.21  1889.5 2354.34  2006.3 2371.51
#Mann= 15 ,-1 , 0
       0     .08       0   104.4    .016       0   228.5     .12       0
   344.2     .08       0   488.4    .016       0   808.1     .08       0
   928.6     .12       0  1007.8     .06       0  1199.8    .045       0
    1249     .04       0  1360.5     .08       0  1492.7    .016       0
  1515.3     .09       0  1819.4    .016       0  1889.5     .12       0
#XS Ineff= 2 , 0
          703.04 2188.99
Permanent Ineff=
       F       F
#Block Obstruct= 6 ,-1
  395.98  460.252208.542  560.73  593.022207.716  604.95  672.97 2207.43
   845.2  887.332207.546 1146.62    11952208.855  1511.6 1547.652251.437
Bank Sta=1249,1360.5
XS Rating Curve= 0 ,0
Exp/Cntr=0.3,0.1

Type RM Length L Ch R = 1 ,15707   ,820.7,840.2,849.3
Node Name=T
XS GIS Cut Line= 2
      2098805.94      443970.093     2098825.516      445862.434
#Sta/Elev= 30
       0 2249.07   146.82221.107   236.6 2205.12   266.1 2201.59   295.6 2197.19
   341.8 2190.35   393.6 2183.69   472.92176.818   561.5 2176.44   882.6 2175.58
   915.9  2175.7  1034.1 2174.41  1062.6 2170.12  1112.2 2174.41  1167.6  2172.1
  1180.7 2165.64    1222 2164.59  1249.6 2165.47  1262.7 2171.76  1302.1 2181.69
    1359 2228.37  1395.5 2235.71    1407 2253.39  1462.8 2285.72  1557.9 2330.86
  1626.8  2354.7  1672.7 2388.46  1693.4 2388.68  1820.3 2392.79  1892.4 2410.36
#Mann= 18 ,-1 , 0
       0     .12       0   146.8     .08       0   236.6    .016       0
   266.1     .08       0   295.6     .12       0   341.8    .016       0
   393.6     .12       0   472.9     .08       0   561.5     .08       0
   882.6     .12       0   915.9     .08       0  1034.1    .016       0
  1112.2     .06       0  1167.6     .04       0  1262.7     .06       0
    1359    .016       0  1395.5     .09       0  1693.4     .06       0
#Block Obstruct= 11 ,-1
   184.2  218.732233.549  284.17     3102220.812  399.04  447.892205.599
  496.77  544.842201.686  614.01  633.612200.892  640.09  672.322201.426
  691.16  730.25 2201.95  747.11   777.4 2201.54  796.04  872.682200.542
  926.35  950.522200.049  963.94 1018.022199.625
Bank Sta=1167.6,1262.7
XS Rating Curve= 0 ,0
Exp/Cntr=0.3,0.1

Type RM Length L Ch R = 1 ,14867   ,778.7,809.3,831.7
XS GIS Cut Line= 2
     2098159.934      443891.789     2097879.345      445790.656
#Sta/Elev= 30
       0 2341.65   127.8 2294.94   139.1 2286.96   168.9 2279.07   340.6 2218.44
   347.8 2216.16   349.6 2215.59   454.8 2191.85   537.5 2184.98   553.4 2185.11
   692.62180.183   763.2 2167.72   786.1 2166.71   797.52170.902   915.4 2172.53
   931.2 2172.42  1154.22173.276  1179.2 2166.43  1193.3 2161.82  1228.7 2161.28
 1262.37  2166.4  1274.2 2172.23  1323.3 2176.82  1393.1 2197.22  1424.72197.177
  1447.8 2209.24  1496.9 2221.79  1608.3 2237.21  1647.6 2249.03  1919.5 2286.73
#Mann= 19 ,-1 , 0
       0     .12       0   139.1    .016       0   168.9     .12       0
   340.6     .06       0   347.8     .12       0   349.6     .06       0
   454.8     .08       0   537.5    .016       0   553.4     .08       0
   692.6     .06       0   797.5     .08       0   915.4    .016       0
   931.2     .08       0  1154.2     .08       0  1179.2    .035       0
 1262.37     .03       0  1274.2     .08       0  1393.1    .016       0
  1424.7     .12       0
#XS Ineff= 2 , 0
           887.7  2172.6
Permanent Ineff=
       F       F
#Block Obstruct= 3 ,-1
  464.61  512.072210.558  645.48  714.27 2204.07  827.64  848.522197.415
Bank Sta=1179.2,1262.37
XS Rating Curve= 0 ,0
Exp/Cntr=0.5,0.3

Type RM Length L Ch R = 1 ,14057   ,185.9,178.7,180.1
BEGIN DESCRIPTION:
Merged DS Survey CHE022BU
END DESCRIPTION:
XS GIS Cut Line= 2
     2097873.358       443740.45     2096816.257      445534.911
#Sta/Elev= 30
       0 2361.66   134.5 2315.69   278.8 2254.69   403.9 2218.94   475.6 2205.34
   580.6  2197.2   692.9 2193.69   746.7 2191.12   770.2  2187.4  1003.1 2177.43
  1068.5 2169.75  1095.2 2170.11  1115.6 2169.36  1282.4 2163.06  1310.2 2156.96
  1373.8 2157.07 1386.68 2163.02  1397.2 2172.22  1432.4 2172.68  1474.4 2171.92
  1495.6 2176.07  1521.8 2176.71  1526.3  2182.8  1538.2  2202.4  1577.6 2244.99
  1623.5 2280.56  1715.3 2325.03  1882.6 2425.19  1954.8 2456.86  2082.7 2479.56
#Mann= 16 ,-1 , 0
       0     .12       0   403.9     .06       0   580.6     .12       0
   692.9     .08       0   746.7    .016       0   770.2     .06       0
  1003.1     .08       0  1068.5     .06       0  1095.2    .016       0
  1115.6     .06       0  1282.4    .035       0 1386.68     .08       0
  1432.4    .016       0  1474.4     .08       0  1495.6    .016       0
  1526.3     .12       0
#XS Ineff= 2 , 0
            1175  2181.5    1445         2174.01
Permanent Ineff=
       F       F
#Block Obstruct= 4 ,-1
  423.04  466.552231.864  641.03  703.312217.921 1026.39 1047.07 2196.27
 1403.18 1440.742197.235
Bank Sta=1282.4,1386.68
XS Rating Curve= 0 ,0
Exp/Cntr=0.5,0.3

Type RM Length L Ch R = 3 ,13945.5 ,,,
BEGIN DESCRIPTION:
Bridge Avenue. Merged DS Survey CHE020RP
END DESCRIPTION:
Bridge Culvert--1,0,-1,-1, 0
Deck Dist Width WeirC Skew NumUp NumDn MinLoCord MaxHiCord MaxSubmerge Is_Ogee
96,28,2.6,0, 60, 60, , , , 0, ,,,
      -8    28.1    54.3      74   129.8   198.7   208.5   218.4   251.2   267.6
   277.4   297.1   310.2   316.8   336.4   349.6   369.2   411.9   461.1   484.1
     507   628.4   654.6     717   838.4 1135.68  1170.1 1170.11 1186.25  1220.6
  1386.4 1386.41 1436.62 1436.63 1479.85  1537.1  1540.4  1550.2  1563.3  1579.7
  1599.4  1609.2  1622.4  1632.2  1645.3  1691.3  1707.7  1740.5  1753.6  1773.3
  1783.1  1809.4    1829  1861.8  1894.6  1904.5  1914.3  1989.8  2042.3  2088.2
 2360.74 2351.55 2342.85 2334.28 2313.75  2285.2 2280.89 2274.23 2265.55 2258.04
 2252.22 2250.81  2242.3 2239.36  2235.9 2229.53 2226.56 2215.84 2210.51 2210.17
 2207.11 2201.58 2197.14 2194.22 2191.83 2182.25  2181.5  2183.7 2183.01  2182.2
  2178.2  2178.2 2176.25 2174.05    2174 2177.66 2179.18 2195.66 2206.73 2223.06
 2250.04 2259.48 2268.84  2278.2 2286.84 2307.78 2316.91 2337.61 2341.55 2356.44
 2365.93 2387.52 2397.31  2409.9 2418.86 2420.35 2424.15 2445.29 2465.31 2486.82
       0       0       0       0       0       0       0       0       0       0
       0       0       0       0       0       0       0       0       0       0
       0       0       0       0       0       0       0       0       0  2176.5
  2172.5       0       0       0       0       0       0       0       0       0
       0       0       0       0       0       0       0       0       0       0
       0       0       0       0       0       0       0       0       0       0
   344.7   351.3   354.6   374.2   403.8     430   469.4   489.1   498.9     512
   633.4   662.9   725.2   758.1   843.4 1140.68 1178.25 1178.26 1191.25  1228.8
  1393.2 1393.21 1407.18    1445 1445.01 1484.85  1542.1  1545.4  1548.6  1555.2
  1558.5  1568.3  1584.7  1604.4  1614.2  1627.4  1637.2  1650.3  1696.3  1712.7
  1745.5  1758.6  1765.1  1778.3  1788.1  1794.7  1811.1  1814.4    1834  1866.8
  1899.6  1909.5  1919.3  1948.8  1994.8  2011.2  2027.6  2047.3  2063.7  2093.2
 2234.75  2230.8 2229.53 2226.56 2218.42  2214.1 2210.26 2210.17 2208.35 2207.11
 2201.58 2196.92  2194.1 2194.18 2191.83 2182.25  2181.5  2183.7 2183.01  2182.2
  2178.2  2178.2 2177.12 2176.25 2174.05    2174 2177.66 2179.18 2184.01 2195.66
 2199.07 2206.73 2223.06 2250.04 2259.48 2268.84  2278.2 2286.84 2307.78 2316.91
 2337.61 2341.55 2347.12 2356.44 2365.93 2371.06 2385.51 2387.52 2397.31  2409.9
 2418.86 2420.35 2424.15 2431.71 2445.29 2451.82 2457.32 2465.31  2472.5 2486.82
       0       0       0       0       0       0       0       0       0       0
       0       0       0       0       0       0       0       0       0  2176.5
  2172.5       0       0       0       0       0       0       0       0       0
       0       0       0       0       0       0       0       0       0       0
       0       0       0       0       0       0       0       0       0       0
       0       0       0       0       0       0       0       0       0       0
Pier Skew, UpSta & Num, DnSta & Num=  ,1307.05, 2 ,1308.69, 2 , 0 , 0 , 0 ,0,0
       3       3
    2140    2177
       3       3
    2140    2177
BR Coef=-1 , 1 , 0 ,1.25, 0 ,,,0.8,0,1,0,
WSPro=,,,, 1 ,,,, 0 ,,,, 0 ,,,,-1 ,-1 ,-1 , 0 , 0 , 0 , 0 , 0
BR U #Sta/Elev= 30
       0 2361.66   134.5 2315.69   278.8 2254.69   403.9 2218.94   475.6 2205.34
   580.6  2197.2   692.9 2193.69   746.7 2191.12   770.2  2187.4  1003.1 2177.43
  1068.5 2169.75  1095.2 2170.11  1115.6 2169.36  1282.4 2163.06  1310.2 2156.96
  1373.8 2157.07 1386.68 2163.02  1397.2 2172.22  1432.4 2172.68  1474.4 2171.92
  1495.6 2176.07  1521.8 2176.71  1526.3  2182.8  1538.2  2202.4  1577.6 2244.99
  1623.5 2280.56  1715.3 2325.03  1882.6 2425.19  1954.8 2456.86  2082.7 2479.56
BR U #Mann= 16
       0     .12   403.9     .06   580.6     .12   692.9     .08   746.7    .016
   770.2     .06  1003.1     .08  1068.5     .06  1095.2    .016  1115.6     .06
  1282.4     .03 1386.68     .08  1432.4    .016  1474.4     .08  1495.6    .016
  1526.3     .12
BR D #Sta/Elev= 30
       0 2342.95   268.7 2251.79   314.6 2240.98   580.7 2212.56   646.3  2202.1
   678.4  2197.4   725.6  2192.9   791.4 2185.41   850.7 2181.68   920.6 2179.66
   973.3 2178.73  1040.1 2176.24  1077.6 2174.09  1143.7 2170.37  1230.1 2169.56
  1288.9  2162.3  1364.4 2155.66  1388.4 2156.19  1393.8 2162.47  1405.9 2170.45
  1474.4 2172.55  1476.4 2172.83  1520.6 2177.75  1530.7 2193.32  1576.3 2242.94
  1638.5  2286.5  1730.3  2336.7  1746.7 2341.67  1779.4 2363.91    2058 2483.36
BR D #Mann= 19
       0     .12   314.6    .016   580.7     .08   646.3     .12   678.4    .016
   725.6     .06   791.4     .08   850.7     .06   920.6    .016   973.3     .06
  1040.1    .016  1077.6     .06  1143.7     .08  1230.1     .06  1288.9     .03
  1393.8     .06  1474.4     .08  1476.4    .016  1530.7     .12
BC Design=,, 0 ,, 0 ,,0,,,,
BC HTab HWMax=0
BC HTab TWMax=0
BC HTab MaxFlow=0
BC Use User HTab Curves=0
BC User HTab FreeFlow(D)= 0

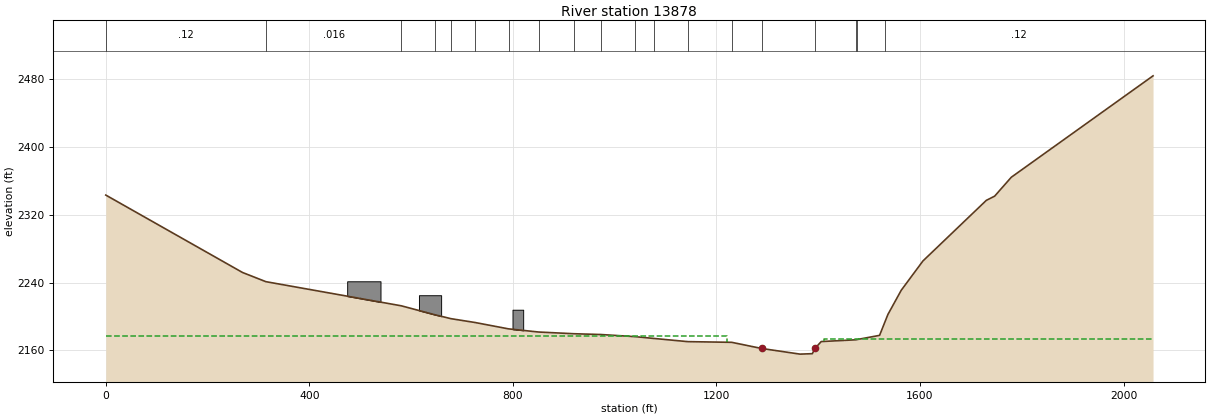
Type RM Length L Ch R = 1 ,13878   ,478.8,493.3,500.4
BEGIN DESCRIPTION:
Merged US Survey CHE018BD
END DESCRIPTION:
XS GIS Cut Line= 2
     2097719.865       443682.86     2096656.239      445444.695
#Sta/Elev= 30
       0 2342.95   268.7 2251.79   314.6 2240.98   580.7 2212.56   646.3  2202.1
   678.4  2197.4   725.6  2192.9   791.4 2185.41   850.7 2181.68   920.6 2179.66
   973.3 2178.73  1040.1 2176.24  1077.6 2174.09  1143.7 2170.37  1230.1 2169.56
  1288.9  2162.3  1364.4 2155.66  1388.4 2156.19  1393.8 2162.47  1405.9 2170.45
  1474.4 2172.55  1476.4 2172.83  1520.6 2177.75    1537  2202.4  1563.2 2230.89
  1605.8 2265.36  1730.3  2336.7  1746.7 2341.67  1779.4 2363.91    2058 2483.36
#Mann= 19 ,-1 , 0
       0     .12       0   314.6    .016       0   580.7     .08       0
   646.3     .12       0   678.4    .016       0   725.6     .06       0
   791.4     .08       0   850.7     .06       0   920.6    .016       0
   973.3     .06       0  1040.1    .016       0  1077.6     .06       0
  1143.7     .08       0  1230.1     .06       0  1288.9    .035       0
  1393.8     .06       0  1474.4     .08       0  1476.4    .016       0
  1530.7     .12       0
#XS Ineff= 2 , 0
            1220  2177.5    1411          2173.6
Permanent Ineff=
       F       F
#Block Obstruct= 3 ,-1
  474.36  539.872241.434  615.38  659.012225.018  799.23  820.252207.974
Bank Sta=1288.9,1393.8
XS Rating Curve= 0 ,0
Exp/Cntr=0.5,0.3