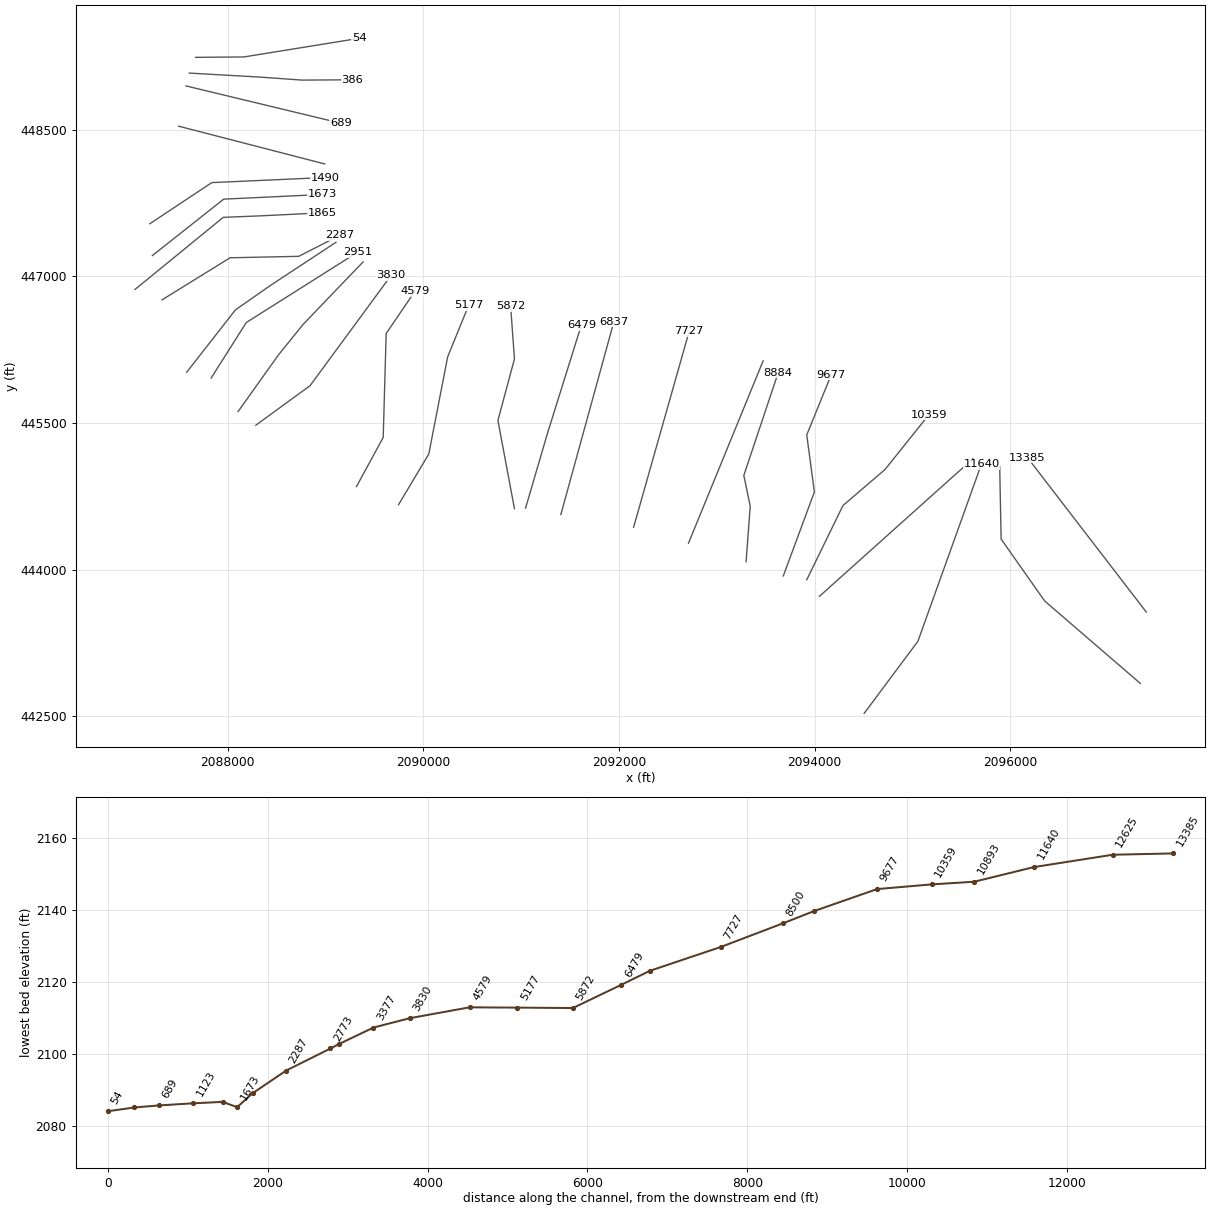
HEC-RAS study CHERRYRV.prj: CHERRYRV

--- CHERRYRV.g03 (geometry) --- (continued)

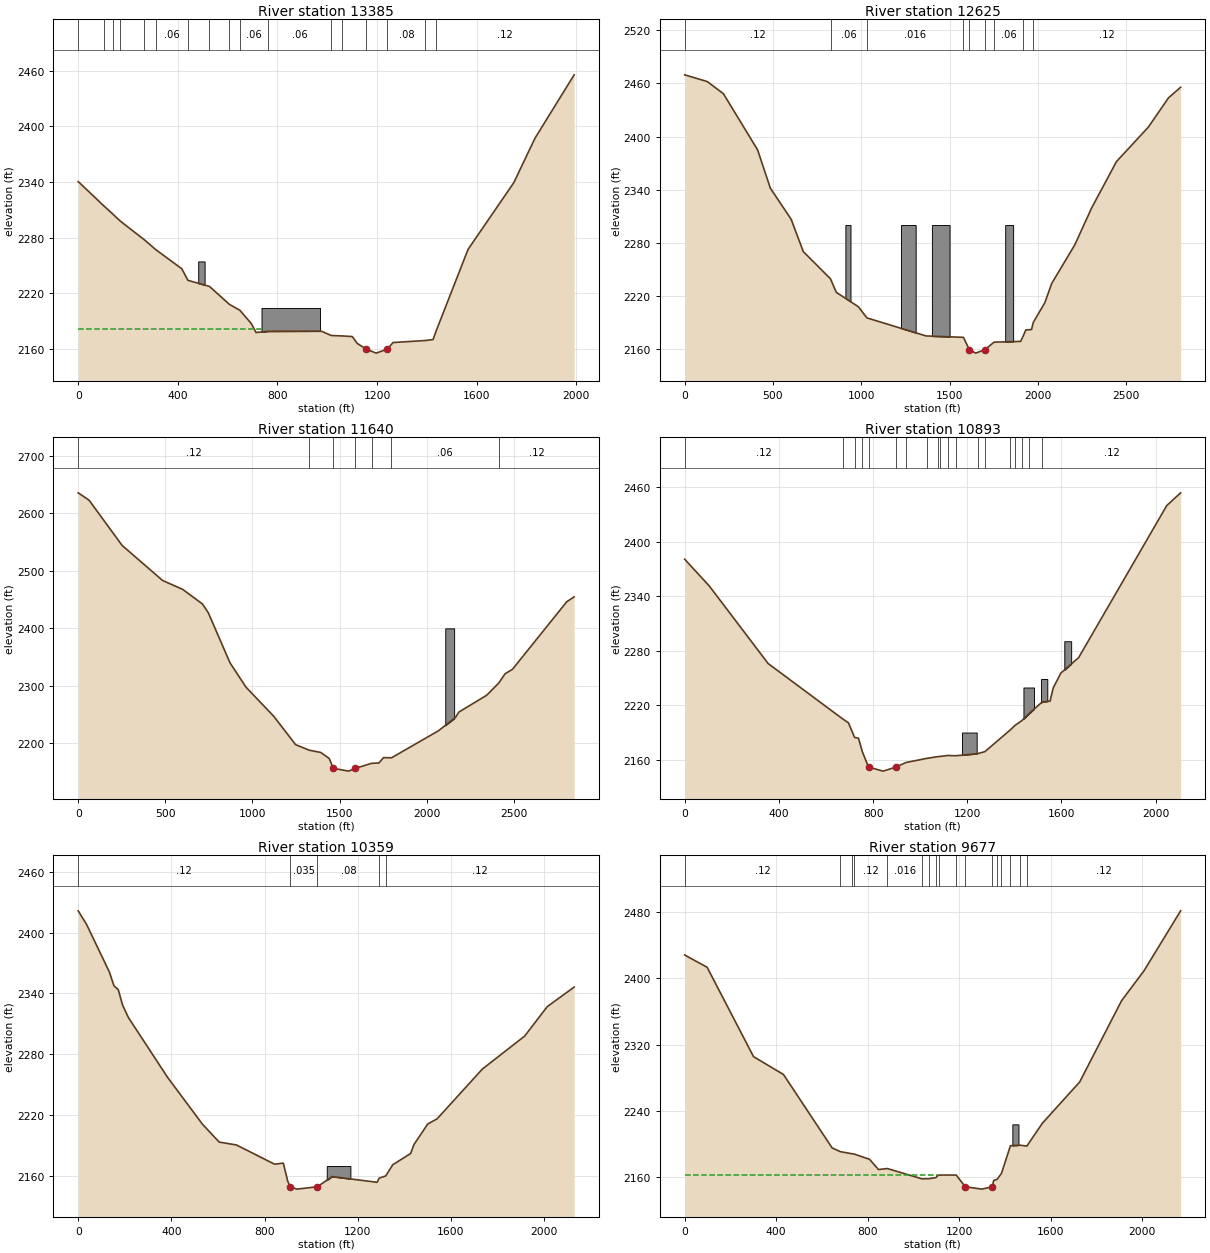
Type RM Length L Ch R = 1 ,13385   ,748.3,760.6,754.4
XS GIS Cut Line= 2
     2097392.223      443565.823     2096178.515       445144.95
#Sta/Elev= 30
       0 2340.63   102.72314.462   137.8 2305.87   168.12298.208   266.22277.706
   311.6  2267.2     416 2246.63   440.6 2234.15   526.9  2227.6   607.5 2208.18
   649.1 2201.91   694.5 2187.76   714.1  2177.9   764.1  2179.2   976.2 2179.37
  1016.5 2174.64  1060.1 2174.21  1100.7 2173.51  1120.3 2166.19 1156.16 2160.05
  1196.5 2155.66 1241.49    2160  1264.4 2167.08  1394.12169.254    1425  2170.3
  1438.4  2180.2  1565.8  2267.6  1749.3  2339.4  1834.4 2387.32  1991.7 2455.69
#Mann= 17 ,-1 , 0
       0     .12       0   102.7     .06       0   137.8     .12       0
   168.1     .06       0   266.2     .12       0   311.6     .06       0
   440.6     .08       0   526.9     .06       0   607.5    .016       0
   649.1     .06       0   764.1     .06       0  1016.5     .08       0
  1060.1     .08       0 1156.16    .035       0 1241.49     .08       0
  1394.1    .016       0  1438.4     .12       0
#XS Ineff= 2 , 0
          734.58  2182.1
Permanent Ineff=
       F       F
#Block Obstruct= 2 ,-1
  481.85  507.612254.523  736.14  970.962204.381
Bank Sta=1156.16,1241.49
XS Rating Curve= 0 ,0
Exp/Cntr=0.3,0.1

Type RM Length L Ch R = 1 ,12625   ,1019.8,984.7,919
XS GIS Cut Line= 4
     2097331.305      442835.412     2096353.513      443678.517
     2095908.164      444312.103     2095893.443      445054.733
#Sta/Elev= 30
       0 2469.74   127.8 2462.14   219.6 2448.36   412.9 2384.94     485 2341.75
   602.9 2306.54   671.8 2269.98   825.8 2239.24   858.5 2223.97   983.1  2207.8
  1032.2 2195.09  1366.2 2174.72  1578.6 2173.12  1611.3 2159.38  1647.5 2155.29
  1699.6 2159.14  1751.8 2167.69  1902.2 2168.53  1918.5 2175.32  1931.6 2181.47
  1964.2 2181.98    1974 2189.96  2039.4 2212.26  2078.6 2234.07  2209.5 2277.78
  2304.4 2319.32  2445.1 2371.73  2625.1 2410.55  2739.6  2443.7  2808.3  2455.7
#Mann= 9 ,-1 , 0
       0     .12       0   825.8     .06       0  1032.2    .016       0
  1578.6     .12       0  1611.3    .045       0  1699.6     .12       0
  1751.8     .06       0  1918.5    .016       0    1974     .12       0
#Block Obstruct= 4 ,-1
     910     939    2300    1225    1308    2300    1400    1500    2300
    1815    1860    2300
Bank Sta=1611.3,1699.6
XS Rating Curve= 0 ,0
Exp/Cntr=0.3,0.1

Type RM Length L Ch R = 1 ,11640   ,773.8,746.7,715.8
Node Name=S
XS GIS Cut Line= 3
     2094507.556      442528.771     2095057.065      443266.306
     2095706.649      445079.313
#Sta/Elev= 30
       0 2635.53    62.2  2622.8     252  2544.1   484.4 2483.15     599  2467.8
   713.5 2442.23   746.3 2427.21   870.6 2340.34   962.3 2297.97  1122.8 2246.94
  1247.3 2197.91  1325.9  2188.2  1391.4 2184.36  1440.5 2173.78  1463.4 2156.81
 1551.11 2151.87  1587.9 2156.44  1682.9  2165.4  1725.5 2166.01  1751.7 2175.36
  1797.5    2175  2066.1  2221.8  2164.3 2244.92    2184 2254.46  2344.5 2283.91
  2413.3 2305.02  2449.3 2321.13  2491.9 2328.89    2803 2446.19  2845.6 2454.74
#Mann= 7 ,-1 , 0
       0     .12       0  1325.9     .06       0  1463.4    .035       0
  1587.9     .07       0  1682.9    .016       0  1797.5     .06       0
  2413.3     .12       0
#Block Obstruct= 1 ,-1
    2106    2157    2400
Bank Sta=1463.4,1587.9
XS Rating Curve= 0 ,0
Exp/Cntr=0.3,0.1

Type RM Length L Ch R = 1 ,10893   ,535.7,534.1,531
XS GIS Cut Line= 2
      2094050.71      443726.972     2095618.418      445133.222
#Sta/Elev= 30
       0 2380.61     105 2351.03   354.3 2266.02  670.59 2205.24   695.4 2200.91
  721.782184.744   738.1 2184.01   754.6 2169.01  781.09 2152.17  842.78 2147.81
  896.65 2152.17  939.532157.274 1027.992161.812 1076.382163.755 1085.872163.999
 1116.46 2164.96 1152.682164.707 1244.582167.056 1275.16 2169.24 1381.862192.913
 1403.292198.152 1431.92 2203.29 1461.232210.752 1518.442223.852  1551.6 2224.72
  1564.7 2239.03  1597.5 2255.56    1673  2272.5    2047 2439.45    2106  2453.5
#Mann= 19 ,-1 , 0
       0     .12       0  670.59     .06       0  721.78    .016       0
   754.6     .12       0  781.09     .03       0  896.65     .12       0
  939.53     .06       0 1027.99    .016       0 1076.38     .06       0
 1085.87     .08       0 1116.46    .016       0 1152.68     .08       0
 1244.58     .06       0 1275.16    .016       0 1381.86     .08       0
 1403.29    .016       0 1431.92     .08       0 1461.23    .016       0
 1518.44     .12       0
#Block Obstruct= 4 ,-1
 1177.74    12402190.224 1438.57 1483.242239.664 1513.41 1539.872249.009
 1612.06 1641.262290.486
Bank Sta=781.09,896.65
XS Rating Curve= 0 ,0
Exp/Cntr=0.3,0.1

Type RM Length L Ch R = 1 ,10359   ,620.3,682.6,727.6
XS GIS Cut Line= 4
2093920.87270224443896.5320275572094290.94202105444655.945108861
2094718.83467092445022.1595389312095169.85665322445584.973294619
#Sta/Elev= 30
       0 2421.42    35.8 2408.07     134    2361   153.6 2347.47   171.8 2343.81
   190.4  2328.6   215.6 2316.19   383.5 2257.33   533.1 2211.18   605.1 2193.46
   679.1 2190.61   843.1 2171.65   880.5 2172.73   899.7 2154.79  909.94  2149.4
  938.92 2147.07  1027.3  2149.4  1089.7 2159.43    1283  2153.8  1292.3  2157.9
  1320.2 2160.08  1350.5 2171.11  1427.3 2182.22  1441.3 2190.97  1500.4 2211.22
  1540.7 2216.34  1735.4  2265.5  1916.7 2297.93  2013.4 2326.92  2129.2 2346.26
#Mann= 5 ,-1 , 0
       0     .12       0  909.94    .035       0  1027.3     .08       0
  1292.3    .016       0  1320.2     .12       0
#Block Obstruct= 1 ,-1
 1067.04 1168.51 2169.82
Bank Sta=909.94,1027.3
XS Rating Curve= 0 ,0
Exp/Cntr(USF)=0,0
Exp/Cntr=0.3,0.1

Type RM Length L Ch R = 1 ,9677    ,787.1,792.1,656.9
XS GIS Cut Line= 4
     2093680.918      443935.305     2093998.626       444794.68
     2093920.501      445378.014     2094170.501      445992.597
#Sta/Elev= 30
       0 2428.1498.19995 2413.26     301 2305.54431.8999    2284   644.6 2195.49
  680.722190.931  731.742188.406   739.52188.176   808.2 2181.73   847.5 2169.38
885.64992170.598 1038.152158.161 1067.952158.388 1097.752159.576 1109.76 2162.71
 1187.152162.745  1226.8 2148.66 1299.23 2145.77  1344.6 2148.53  1351.1  2156.3
 1365.952157.528 1385.072164.849 1424.262198.114 1464.142198.793 1496.052197.696
  1563.6 2225.14    1727 2275.01    1910 2372.95  2008.1 2409.04  2168.2 2481.36
#Mann= 17 ,-1 , 0
       0     .12       0  680.72    .016       0  731.74     .08       0
   739.5     .12       0885.6499    .016       0 1038.15     .06       0
 1067.95     .08       0 1097.75     .12       0 1109.76     .08       0
 1187.15     .06       0  1226.8    .035       0  1344.6     .06       0
 1365.95    .016       0 1385.07     .12       0 1424.26     .08       0
 1464.14    .016       0 1496.05     .12       0
#XS Ineff= 2 , 0
         1105.08 2162.79
Permanent Ineff=
       F       F
#Block Obstruct= 1 ,-1
 1432.57 1459.312223.878
Bank Sta=1226.8,1344.6
XS Rating Curve= 0 ,0
Exp/Cntr=0.3,0.1

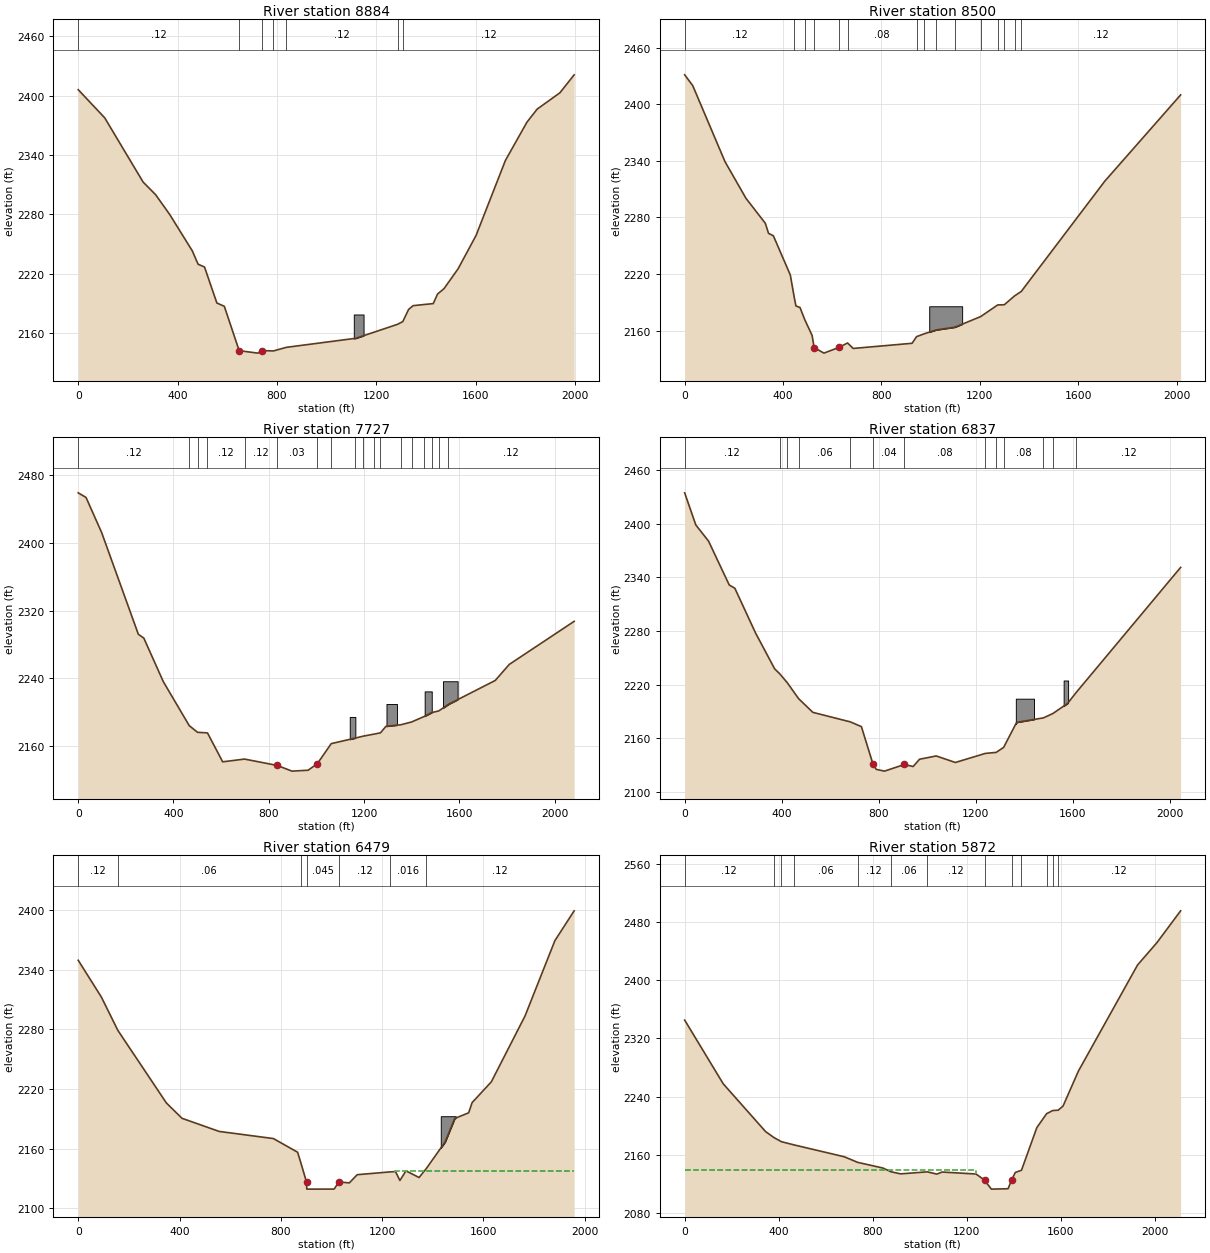
Type RM Length L Ch R = 1 ,8884    ,426,384.3,280.1
XS GIS Cut Line= 4
2093300.23561549444081.566686961 2093342.6393916444648.235331386
2093277.10628306444964.3362078682093627.90115818 446012.86594449
#Sta/Elev= 30
       0 2406.07   106.7 2377.61   261.3 2312.63   311.5 2299.92   368.5  2279.8
   459.6 2242.97   482.6 2229.55   508.5 2226.73   558.3 2190.31   588.2 2187.01
  648.09 2142.11  723.08 2139.63   738.1  2142.2   785.9 2141.84     838 2145.48
  1118.1 2154.66  1285.5 2168.76  1306.8 2171.54  1330.1 2183.78  1348.2 2187.65
  1429.4 2189.73  1446.7 2199.41  1472.7  2204.8  1529.8 2225.06  1601.9  2258.7
    1720 2334.55  1806.5 2373.15    1848 2386.46  1939.3  2402.9  1996.7 2421.09
#Mann= 7 ,-1 , 0
       0     .12       0  648.09    .035       0   738.1     .12       0
   785.9    .016       0     838     .12       0  1285.5    .016       0
  1306.8     .12       0
#Block Obstruct= 1 ,-1
 1109.47 1148.83 2178.72
Bank Sta=648.09,738.1
XS Rating Curve= 0 ,0
Exp/Cntr(USF)=0,0
Exp/Cntr=0.3,0.1

Type RM Length L Ch R = 1 ,8500    ,711.1,773.3,732.7
XS GIS Cut Line= 2
     2092711.296      444270.257     2093474.758      446136.497
#Sta/Elev= 30
       0 2431.06    32.8  2419.6   163.9 2339.12   249.2 2300.28   327.9 2273.82
     341 2263.18   360.6 2260.57   429.5 2219.07   445.9 2194.76   452.4 2186.24
   468.8 2184.65     488 2171.88     518  2155.1  526.35 2142.16   566.3 2136.28
   626.2 2142.25   662.3 2147.03   685.2 2141.24   924.6  2146.7   942.8 2153.73
     975 2156.85  1022.7 2160.83  1098.8 2163.75  1203.2 2174.96  1272.8 2187.34
  1299.5 2187.52    1341 2196.82  1368.5 2201.63  1708.2 2318.44  2016.4  2409.8
#Mann= 15 ,-1 , 0
       0     .12       0   445.9    .016       0     488     .12       0
  526.35    .035       0   626.2     .06       0   662.3     .08       0
   942.8    .016       0     975     .09       0  1022.7     .08       0
  1098.8    .016       0  1203.2     .09       0  1272.8    .016       0
  1299.5     .08       0    1341    .016       0  1368.5     .12       0
#Block Obstruct= 1 ,-1
  994.27 1128.162185.926
Bank Sta=526.35,626.2
XS Rating Curve= 0 ,0
Exp/Cntr=0.3,0.1

Type RM Length L Ch R = 1 ,7727    ,781.1,889.8,810.7
XS GIS Cut Line= 2
     2092150.119       444433.39     2092717.821      446436.662
#Sta/Elev= 30
       0 2459.46    32.8 2454.02    98.4 2412.41   252.5 2291.87   275.4 2287.38
   357.4 2235.72   466.3 2183.59   501.1 2175.75   542.72175.053   606.6 2140.78
   698.4 2144.04   836.1 2136.47   897.4 2129.76     965 2130.81  1003.4 2138.37
  1062.4 2162.35  1161.22168.772  1195.9 2171.14  1241.72173.587  1268.92175.093
  1291.9 2182.79  1355.1 2184.72  1399.4 2187.96  1452.8 2194.51  1483.7 2199.05
  1514.2 2201.12  1554.6 2208.88    1751  2237.2    1810 2256.22  2082.2 2307.22
#Mann= 18 ,-1 , 0
       0     .12       0   466.3    .016       0   501.1     .06       0
   542.7     .12       0   698.4     .12       0   836.1     .03       0
  1003.4     .08       0  1062.4     .06       0  1161.2     .06       0
  1195.9    .016       0  1241.7     .06       0  1268.9     .08       0
  1355.1    .016       0  1399.4     .06       0  1452.8     .08       0
  1483.7    .016       0  1514.2     .08       0  1554.6     .12       0
#Block Obstruct= 4 ,-1
 1140.05 1163.58 2193.96  1294.2 1338.212209.319 1454.56 1484.31 2224.24
 1531.35 1592.952236.236
Bank Sta=836.1,1003.4
XS Rating Curve= 0 ,0
Exp/Cntr=0.3,0.1

Type RM Length L Ch R = 1 ,6837    ,365.4,357.6,364
XS GIS Cut Line= 2
     2091406.233      444563.897     2091947.834      446534.542
#Sta/Elev= 30
       0 2434.38    45.9 2398.45    98.4 2380.38   183.7 2331.28   206.7 2327.67
     292 2277.68   370.7 2237.57   392.3 2231.82   422.7 2222.05   469.7 2204.12
   528.2 2188.87   682.8  2178.2   728.3 2172.89  775.85 2131.11   789.5 2125.11
   823.4 2123.13   905.4 2130.55   941.5 2128.28   967.7 2136.41  1036.6 2140.11
  1115.4  2132.8    1239 2142.94  1283.6 2144.08  1314.3 2149.65  1367.9 2177.61
  1478.6  2182.7  1517.6  2187.6  1577.9 2198.87    1614 2211.29  2043.7 2350.96
#Mann= 13 ,-1 , 0
       0     .12       0   392.3    .016       0   422.7     .12       0
   469.7     .06       0   682.8     .12       0  775.85     .04       0
   905.4     .08       0    1239    .016       0  1283.6     .09       0
  1314.3     .08       0  1478.6    .016       0  1517.6     .06       0
    1614     .12       0
#Block Obstruct= 2 ,-1
 1364.59 1439.682204.156 1561.65 1580.112224.488
Bank Sta=775.85,905.4
XS Rating Curve= 0 ,0
Exp/Cntr=0.3,0.1

Type RM Length L Ch R = 1 ,6479    ,591,607.1,569.5
XS GIS Cut Line= 3
  2091045.125704444628.9608876982091268.70925078445392.228857739
2091615.64923717446502.436814163
#Sta/Elev= 30
       0 2349.55    91.7 2312.43   156.7 2278.95   348.1    2206   409.9 2190.52
   556.7 2177.32   770.8 2170.15   866.3 2156.41   878.32146.537   901.8 2126.19
   902.6 2119.29   927.3 2119.26  1010.6 2119.29  1029.7 2126.51  1070.6 2125.52
  1101.8 2133.79  1232.5 2136.62  1253.2 2136.88  1270.3 2127.96  1294.4 2137.63
    1346 2130.95  1373.5 2139.58  1449.1 2166.75  1486.9 2190.31  1541.9 2196.08
  1555.6 2206.33  1631.3 2227.18  1764.6 2293.52  1882.4 2369.28  1958.5  2399.3
#Mann= 7 ,-1 , 0
       0     .12       0   156.7     .06       0   878.3     .12       0
   901.8    .045       0  1029.7     .12       0  1232.5    .016       0
  1373.5     .12       0
#XS Ineff= 2 , 0
                         1250.81         2137.18
Permanent Ineff=
       F       F
#Block Obstruct= 1 ,-1
 1431.73 1490.77 2192.63
Bank Sta=901.8,1029.7
XS Rating Curve= 0 ,0
Exp/Cntr(USF)=0,0
Exp/Cntr=0.3,0.1

Type RM Length L Ch R = 1 ,5872    ,686.7,694.8,695.1
Node Name=R
XS GIS Cut Line= 4
     2090931.786      444623.673     2090762.515      445526.451
     2090931.786      446155.791     2090892.724      446693.986
#Sta/Elev= 30
       0 2345.25     164 2257.65   344.4 2191.86  379.292183.828  411.152178.063
  466.442173.535     679 2157.31  735.792149.633   843.1 2141.82  876.592136.775
   918.5 2133.77 1032.112136.582  1072.4 2133.48  1095.4 2136.29  1239.4 2133.58
  1275.5  2125.3 1304.62  2112.8 1375.79 2113.32 1391.25 2125.53  1406.5 2135.73
 1432.842138.774  1498.2 2197.47 1539.922216.563 1565.912220.892 1588.572221.308
  1609.5 2226.94  1674.9 2275.07  1926.7 2421.07  2008.4 2451.52  2109.8 2495.51
#Mann= 13 ,-1 , 0
       0     .12       0  379.29    .016       0  411.15     .12       0
  466.44     .06       0  735.79     .12       0  876.59     .06       0
 1032.11     .12       0  1275.5    .045       0 1391.25    .016       0
 1432.84     .12       0 1539.92     .08       0 1565.91    .016       0
 1588.57     .12       0
#XS Ineff= 2 , 0
         1240.57 2139.59
Permanent Ineff=
       F       F
Bank Sta=1275.5,1391.25
XS Rating Curve= 0 ,0
Exp/Cntr=0.3,0.1

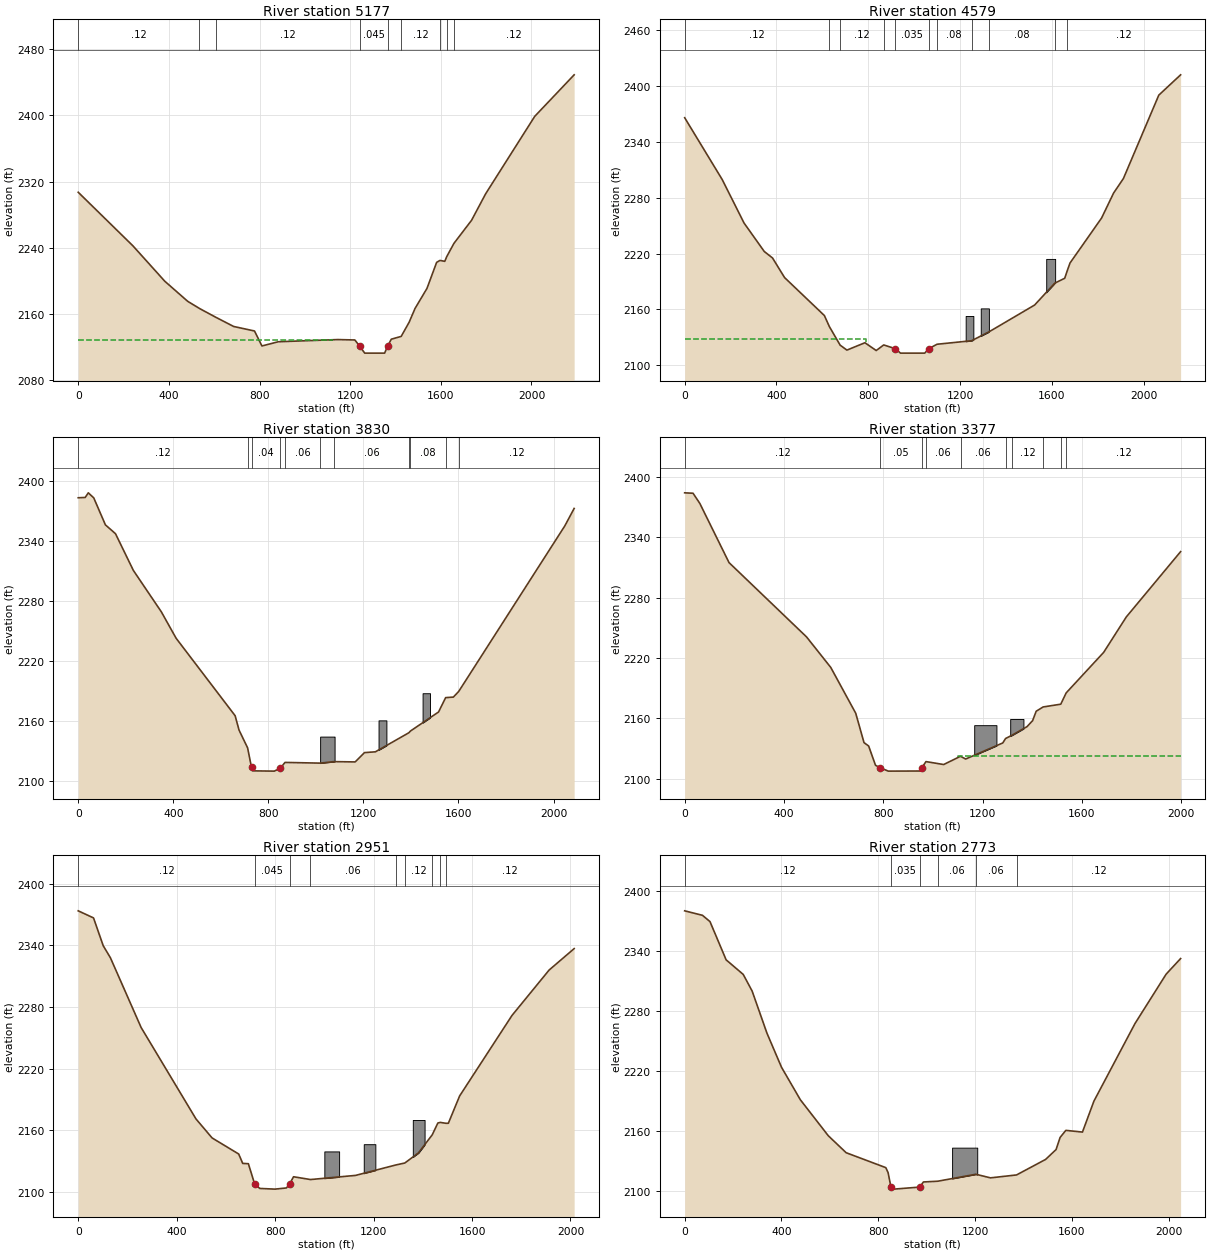
Type RM Length L Ch R = 1 ,5177    ,589.3,598.1,600.2
XS GIS Cut Line= 4
     2089746.499      444663.991      2090055.81      445182.782
     2090248.948      446177.864     2090464.284      446706.415
#Sta/Elev= 30
       0 2307.24   241.6 2242.46     382 2199.78   483.2 2175.49     535 2166.89
   606.5 2156.32     686  2145.1   777.9 2139.67   810.7 2121.57   882.8 2126.66
  1145.3 2129.29  1220.7 2128.82 1242.27 2121.23 1264.31 2112.92 1352.02 2112.92
  1365.1 2121.18  1381.5 2129.74  1425.2 2133.13  1460.2 2150.21  1486.4 2166.93
  1538.9 2191.05  1581.6 2222.54  1596.1 2224.89  1617.6 2223.81    1626  2229.4
  1657.9 2245.46  1735.7 2273.37  1798.1 2305.49  2014.5 2398.92  2188.4 2449.08
#Mann= 9 ,-1 , 0
       0     .12       0     535    .016       0   606.5     .12       0
 1242.27    .045       0  1365.1    .016       0  1425.2     .12       0
  1596.1    .016       0    1626     .06       0  1657.9     .12       0
#XS Ineff= 2 , 0
         1125.05 2129.19
Permanent Ineff=
       F       F
Bank Sta=1242.27,1365.1
XS Rating Curve= 0 ,0
Exp/Cntr=0.3,0.1

Type RM Length L Ch R = 1 ,4579    ,791.4,749.3,627.8
BEGIN DESCRIPTION:
Lowered the XS
END DESCRIPTION:
XS GIS Cut Line= 4
     2089316.186      444849.003     2089589.624      445352.476
     2089620.006      446415.844     2089915.145      446849.872
#Sta/Elev= 30
       0 2366.12   163.7  2299.6   258.6 2252.95     347 2222.27     383 2215.29
   435.4 2194.24   608.9 2153.42   630.3  2141.7   677.7 2121.56   707.1 2116.25
   785.7 2124.18   834.8 2115.79   867.5  2121.8  918.07  2117.8  940.52    2113
 1046.32    2113 1063.47 2117.72  1099.9 2122.55  1250.5 2126.33  1328.2 2136.14
  1525.4 2164.74  1613.3 2188.28  1656.4 2193.49  1667.4 2201.51  1679.4 2209.85
  1817.2  2258.3  1869.6 2285.17  1912.3 2300.76  2066.5 2390.41  2161.6 2412.25
#Mann= 11 ,-1 , 0
       0     .12       0   630.3    .016       0   677.7     .12       0
   867.5     .12       0  918.07    .035       0 1063.47     .12       0
  1099.9     .08       0  1250.5     .06       0  1328.2     .08       0
  1613.3    .016       0  1667.4     .12       0
#XS Ineff= 2 , 0
          789.75 2127.71
Permanent Ineff=
       F       F
#Block Obstruct= 3 ,-1
 1224.76 1258.212152.946 1290.48 1325.932161.095 1575.79 1614.732214.305
Bank Sta=918.07,1063.47
XS Rating Curve= 0 ,0
Exp/Cntr=0.3,0.1

Type RM Length L Ch R = 1 ,3830    ,451.3,452.8,436.4
BEGIN DESCRIPTION:
Lowered the XS
END DESCRIPTION:
XS GIS Cut Line= 3
     2088287.133      445477.441     2088841.784       445882.01
     2089670.499       447010.89
#Sta/Elev= 30
       0 2383.63    29.4 2383.95    42.5 2388.58    65.4 2383.54   114.4 2356.52
   156.9 2347.66   232.1  2310.9   349.8 2269.45   411.9 2243.03   660.4 2165.41
   676.7  2151.1   712.8 2133.27   729.2 2113.74  734.55 2110.25  825.16 2109.98
   850.5  2112.9   870.2  2118.7  1017.8 2117.99  1076.8  2119.5  1165.4 2119.19
  1204.7 2128.52  1250.6 2129.31  1391.6 2148.43  1398.2 2150.14  1516.3 2169.18
  1546.2 2183.56  1578.6 2184.09  1601.5 2189.88  2047.6 2355.48  2086.9 2372.95
#Mann= 11 ,-1 , 0
       0     .12       0   712.8     .05       0   729.2     .04       0
   850.5     .05       0   870.2     .06       0  1017.8    .016       0
  1076.8     .06       0  1391.6    .016       0  1398.2     .08       0
  1546.2    .016       0  1601.5     .12       0
#Block Obstruct= 3 ,-1
    1018 1078.842144.538 1263.78 1296.81  2160.8  1449.1 1480.482187.965
Bank Sta=729.2,850.5
XS Rating Curve= 0 ,0
Exp/Cntr=0.3,0.1

Type RM Length L Ch R = 1 ,3377    ,452.1,426.2,387.9
BEGIN DESCRIPTION:
Manning's in the channel bumped to account for island in the middle
END DESCRIPTION:
XS GIS Cut Line= 5
2088106.43787657445618.0299668292088516.76037609446194.699425609
2088767.38979471446505.213749568 2089055.7245241  446806.8562357
2089383.98252371447148.421992054
#Sta/Elev= 30
       0 2384.17    33.7 2383.75    60.9  2373.7   178.6  2314.8     491 2240.85
   588.5 2210.52   689.1 2164.93   722.4 2135.75   741.1 2132.36   768.8 2113.17
  788.52 2110.72  820.09 2107.39   951.1 2107.51   954.8 2110.62   972.1 2116.86
  1043.4 2113.96  1111.1 2122.14    1132 2119.43  1281.4 2135.42  1292.7 2139.83
  1319.9 2143.27  1378.9 2151.59  1401.6  2157.6    1416 2166.95  1443.9  2171.2
  1515.1 2173.97  1536.7 2185.16  1687.9 2225.52  1778.9 2260.69  1997.8 2325.69
#Mann= 10 ,-1 , 0
       0     .12       0  788.52     .05       0   954.8     .12       0
   972.1     .06       0  1111.1     .06       0  1292.7    .016       0
  1319.9     .12       0  1443.9    .016       0  1515.1    .016       0
  1536.7     .12       0
#XS Ineff= 2 , 0
                         1102.04          2122.8
Permanent Ineff=
       F       F
#Block Obstruct= 2 ,-1
 1166.31 1255.862153.093  1311.3 1364.61 2159.28
Bank Sta=788.52,954.8
XS Rating Curve= 0 ,0
Exp/Cntr(USF)=0,0
Exp/Cntr=0.3,0.1

Type RM Length L Ch R = 1 ,2951    ,101.5,111.6,124.9
XS GIS Cut Line= 3
     2087830.361      445960.314     2088189.253      446528.016
     2089324.658      447245.801
#Sta/Elev= 30
       0 2373.68    62.2 2366.78   101.6 2339.74     131 2327.92   255.6 2260.14
   478.3 2171.23   543.9 2152.68     652 2137.04   668.4 2127.89   691.3 2127.62
  716.97 2107.75   737.9 2103.54  799.31 2102.87  846.08 2104.02  859.01 2107.89
   874.8 2114.91   943.6 2112.19    1127 2116.23  1290.8  2126.4  1326.9 2128.29
  1382.6 2138.18  1438.3 2155.72  1461.2 2167.22    1471 2167.79    1494 2166.93
  1503.8 2166.97  1549.7 2193.57  1762.6 2271.94  1913.3 2316.08  2014.9 2336.91
#Mann= 9 ,-1 , 0
       0     .12       0  716.97    .045       0  859.01     .12       0
   943.6     .06       0  1290.8    .016       0  1326.9     .12       0
  1438.3    .016       0    1471    .016       0    1494     .12       0
#Block Obstruct= 3 ,-1
    1000    1060 2139.57  1160.1  1207.32146.596 1359.38 1407.252170.179
Bank Sta=716.97,859.01
XS Rating Curve= 0 ,0
Exp/Cntr=0.3,0.1

Type RM Length L Ch R = 1 ,2773    ,592.6,552.9,482.8
XS GIS Cut Line= 4
2087579.62256688446019.0549387342088078.61126036446657.668908826
2088445.07725481446913.750821894 2089106.3448538447348.928475019
#Sta/Elev= 30
       02380.318  73.5562375.826  104.652369.503 171.2672331.236 242.0482316.606
 278.8792299.878 340.0092257.752 400.2652223.569  477.912191.116 593.2682155.083
 667.232 2138.05 831.008 2123.12 840.4322118.161 852.2122103.776 863.993 2101.59
  970.78 2103.62 986.509 2108.771045.4112109.5071203.2692116.4791263.584 2112.87
1371.1572115.7941491.3812131.3461534.5842141.2471551.1782153.3371574.8652160.436
1643.5582158.7371690.9322189.7371860.5712267.4151989.3892316.9152049.1322332.526
#Mann= 6 ,-1 , 0
       0     .12       0 852.212    .035       0  970.78     .12       0
1045.411     .06       01203.269     .06       01371.157     .12       0
#Block Obstruct= 1 ,-1
  1104.9 1208.73 2143.16
Bank Sta=852.212,970.78
XS Rating Curve= 0 ,0
Exp/Cntr(USF)=0,0
Exp/Cntr=0.3,0.1

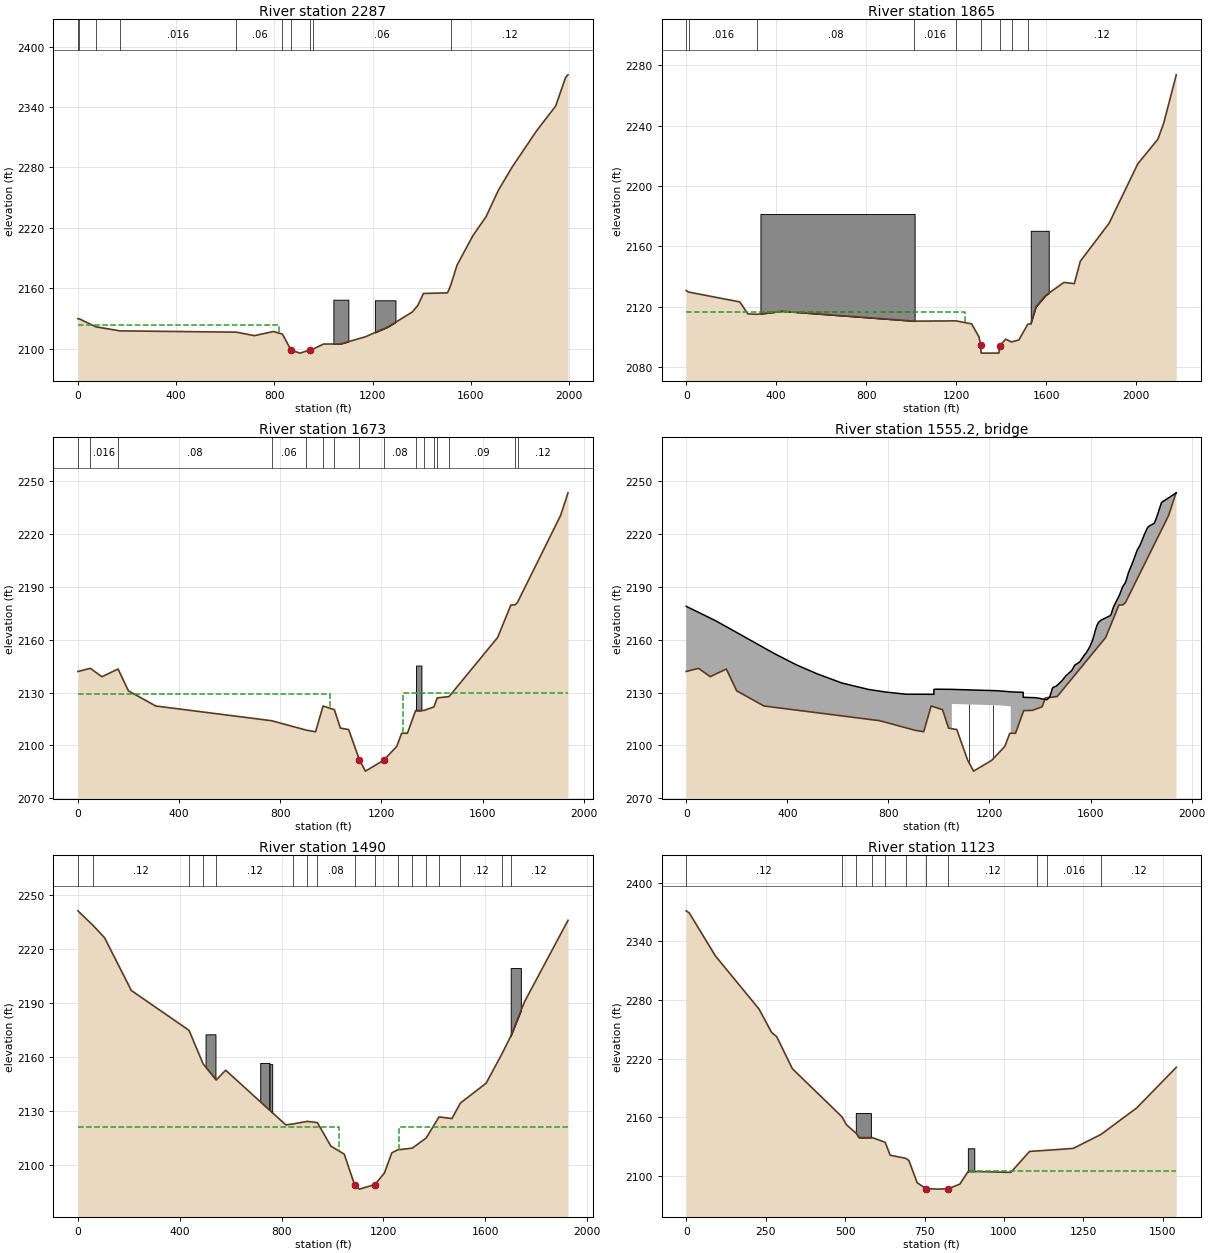
Type RM Length L Ch R = 1 ,2287    ,420.2,421.7,425.1
XS GIS Cut Line= 4
2087326.98105277446759.7910881032088023.97810489447190.834999047
     2088725.909      447205.7742089147.76569603447421.608293614
#Sta/Elev= 30
       0 2129.63   5.174 2129.64  73.171 2121.64 170.8952117.607 645.5242116.308
 718.8172112.851 795.9682116.977 832.6612114.421 868.3972098.271     905 2095.48
   943.9  2098.6     957 2099.49  999.662104.5061068.5732104.5741170.3022111.706
1262.1862121.5041360.6332136.1841383.6042142.7171406.5752154.7341505.0232155.425
1518.1492163.1771543.5212182.8411607.8322212.1131661.4512230.9021711.9222257.396
1768.3242280.5351867.8282316.5451945.2192341.0381985.7572369.5541995.4692372.082
#Mann= 10 ,-1 , 0
       0     .12       0   5.174    .016       0  73.171     .06       0
 170.895    .016       0 645.524     .06       0 832.661     .12       0
 868.397    .045       0   943.9     .12       0     957     .06       0
1518.149     .12       0
#XS Ineff= 2 , 0
          817.89 2123.49
Permanent Ineff=
       F       F
#Block Obstruct= 2 ,-1
 1040.14 1101.142148.589 1209.17 1292.892147.988
Bank Sta=868.397,943.9
XS Rating Curve= 0 ,0
Exp/Cntr=0.5,0.3

Type RM Length L Ch R = 1 ,1865    ,189.6,192.1,189.2
BEGIN DESCRIPTION:
the channel has mud and is not so clean compared to ds and us section. Manning's n bumped to 0.045
END DESCRIPTION:
XS GIS Cut Line= 6
2087051.00607261446866.7408582782087209.67061214 446995.86747792
2087953.50658675447604.4276259712088334.97216984447619.973245345
 2088556.1982917447630.7355972192088965.16766291447651.064484092
#Sta/Elev= 30
       02130.702  10.3992129.677 238.3722123.135 274.0042115.198 315.4542114.906
 427.2222116.9291014.7542110.3741199.6982110.5621268.6532108.5591301.488 2099.97
1308.5112094.2691310.985  2089.2 1323.28 2089.171390.144  2089.21393.4282093.974
1419.6962098.4191445.9652096.583 1478.88 2097.951518.2032108.3151531.3372108.578
1554.325 2119.811597.0262127.3211679.1442136.083 1725.132135.2381751.8852150.138
1879.5172175.2672007.6282214.8122096.3192230.9782122.5982241.7472178.3732273.732
#Mann= 9 ,-1 , 0
       0     .12       0  10.399    .016       0 315.454     .08       0
1014.754    .016       01199.698     .12       01308.511    .045       0
1393.428     .12       01445.965     .08       01518.203     .12       0
#XS Ineff= 2 , 0
         1237.92  2116.7
Permanent Ineff=
       F       F
#Block Obstruct= 2 ,-1
  329.97 1015.322181.441 1531.61 1611.362170.284
Bank Sta=1308.511,1393.428
XS Rating Curve= 0 ,0
Exp/Cntr(USF)=0,0
Exp/Cntr=0.5,0.3

Type RM Length L Ch R = 1 ,1673    ,178.3,182.3,174.6
BEGIN DESCRIPTION:
Merged DS Survey CHE012BU
END DESCRIPTION:
XS GIS Cut Line= 3
     2087229.381      447213.587     2087958.548      447790.844
     2088965.492      447838.587
#Sta/Elev= 30
       0 2141.96    49.1 2143.76      95 2138.99   158.7 2143.37   199.8 2130.96
   307.8 2122.35   765.7 2113.99   903.8 2108.61   939.8  2107.7   969.3 2122.36
  1014.2 2120.25    1038 2109.78  1070.7 2108.95  1113.2  2091.7    1137 2085.33
 1208.69 2091.47  1260.6 2099.35  1280.2 2106.83  1303.1 2106.87  1335.2  2119.7
  1369.4 2119.86  1407.9 2121.85    1421 2126.96  1467.8 2127.71  1659.9 2161.32
  1712.2 2179.76  1728.6 2179.85  1738.4 2181.27  1908.6  2230.6  1938.1 2243.52
#Mann= 16 ,-1 , 0
       0     .12       0    49.1    .016       0   158.7     .08       0
   765.7     .06       0   903.8     .08       0   969.3    .016       0
  1014.2     .12       0  1113.2     .04       0 1208.69     .08       0
  1335.2     .08       0  1369.4    .016       0  1407.9     .08       0
    1421    .016       0  1467.8     .09       0  1728.6    .016       0
  1738.4     .12       0
#XS Ineff= 2 , 0
             998 2129.02  1283.9         2129.88
Permanent Ineff=
       F       F
#Block Obstruct= 1 ,-1
 1337.12 1358.382145.349
Bank Sta=1113.2,1208.69
XS Rating Curve= 0 ,0
Exp/Cntr=0.5,0.3

Type RM Length L Ch R = 3 ,1555.2  ,,,
BEGIN DESCRIPTION:
Nettle Fenwick Road/US Highway 20
Merged DS Survey CHE010RP.
END DESCRIPTION:
Bridge Culvert--1,0,-1,-1, 0
Deck Dist Width WeirC Skew NumUp NumDn MinLoCord MaxHiCord MaxSubmerge Is_Ogee
98,47,2.6,0, 60, 60, , , , 0, ,,,
       0     118   350.7   435.9   517.9   616.2   720.8   789.5   871.2     980
  980.01  992.65    1051 1231.51  1283.9 1298.01 1333.28 1333.29  1383.3  1425.8
  1429.1  1438.9  1448.7    1452    1465    1488    1501  1523.9  1527.2    1537
  1556.6  1576.3  1582.8  1595.9  1605.7    1609  1618.8  1625.3  1631.9  1641.7
  1677.7    1681  1690.8  1713.7  1726.8  1736.6  1739.8  1749.6    1766  1782.4
  1785.6  1795.4  1815.1  1824.9  1831.4  1851.1  1854.3  1860.9  1880.5    1939
 2179.01  2170.7    2152 2145.75 2140.64 2135.42 2131.78 2130.28 2129.03    2129
  2131.8 2131.91  2131.8 2131.03  2130.4  2130.3  2130.1  2127.3 2127.05 2125.96
  2126.1 2127.68 2132.34 2132.94 2133.72 2136.91 2139.34 2142.32 2142.93 2145.55
 2147.35  2151.5 2152.56 2155.81 2158.95 2160.27 2165.36 2168.25    2170 2171.16
 2173.72 2174.38 2178.75 2185.23 2190.14 2192.23 2193.26 2198.08 2203.78 2210.21
 2211.28 2213.72 2220.63 2223.64  2224.6 2226.17 2227.01 2229.42 2238.03 2243.52
                                                                                
                 2123.54 2122.77 2122.14
                                                                                
                                                                                
                                                                                
                                                                                
       0     118   350.7   435.9   517.9   616.2   720.8   789.5   871.2     959
  959.01  992.65    1025  1260.7 1274.91 1314.86 1314.87  1322.4  1383.3  1425.8
  1429.1  1438.9  1448.7    1452    1465    1488    1501  1523.9    1537  1556.6
  1576.3  1582.8  1595.9  1605.7    1609  1618.8  1625.3  1631.9  1641.7  1677.7
    1681  1690.8  1713.7  1726.8  1736.6  1739.8  1746.4  1752.9    1766  1775.8
  1785.6  1795.4  1815.1  1824.9  1831.4  1847.8  1854.3  1864.2  1880.5    1926
 2179.01  2170.7    2152 2145.75 2140.64 2135.42 2131.78 2130.28 2129.03    2129
  2131.8 2131.91  2131.8  2130.8 2130.48  2130.3  2127.5 2127.25 2127.05 2125.96
  2126.1 2127.68 2132.34 2132.94 2133.72 2136.91 2139.34 2142.32 2145.55 2147.35
  2151.5 2152.56 2155.81 2158.95 2160.27 2165.36 2168.25    2170 2171.16 2173.72
 2174.38 2178.75 2185.23 2190.14 2192.23 2193.26 2196.61 2199.38 2203.78 2207.77
 2211.28 2213.72 2220.63 2223.64  2224.6 2225.73 2227.01 2230.79 2238.03 2235.79
                                                                                
                 2123.54 2122.54
                                                                                
                                                                                
                                                                                
                                                                                
Pier Skew, UpSta & Num, DnSta & Num=  ,1119.31, 2 ,1098.91, 2 , 0 , 0 , 0 ,0,0
       3       3
    2080  2126.7
       3       3
    2080  2126.7
Pier Skew, UpSta & Num, DnSta & Num=  ,1213.59, 2 ,1192.02, 2 , 0 , 0 , 0 ,0,0
       3       3
    2080  2126.7
       3       3
    2080  2126.7
BR Coef=-1 , 1 , 0 ,, 0 ,,,0.8,-1,1.33,0,
WSPro=,,,, 1 ,,,, 0 ,,,, 0 ,,,,-1 ,-1 ,-1 , 0 , 0 , 0 , 0 , 0
BR U #Sta/Elev= 30
       0 2141.96    49.1 2143.76      95 2138.99   158.7 2143.37   199.8 2130.96
   307.8 2122.35   765.7 2113.99   903.8 2108.61   939.8  2107.7   969.3 2122.36
  1014.2 2120.25    1038 2109.78  1070.7 2108.95  1113.2  2091.7    1137 2085.33
 1208.69 2091.47  1260.6 2099.35  1280.2 2106.83  1303.1 2106.87  1335.2  2119.7
  1369.4 2119.86  1407.9 2121.85    1421 2126.96  1467.8 2127.71  1659.9 2161.32
  1712.2 2179.76  1728.6 2179.85  1738.4 2181.27  1908.6  2230.6  1938.1 2243.52
BR U #Mann= 16
       0     .12    49.1    .016   158.7     .08   765.7     .06   903.8     .08
   969.3    .016  1014.2     .12  1113.2    .035 1208.69     .08  1335.2     .08
  1369.4    .016  1407.9     .08    1421    .016  1467.8     .09  1728.6    .016
  1738.4     .12
BR D #Sta/Elev= 30
       0 2241.04    60.7 2232.78   104.9 2226.08   209.9 2196.88   436.4 2174.81
   492.2 2156.13   543.2 2147.27   580.4  2152.7   816.6 2122.41   843.3 2122.87
   900.9 2124.35   940.7 2123.65   993.7 2110.64  1046.1  2106.2  1086.7 2089.26
  1105.8 2086.79 1166.32 2089.31    1204 2095.71  1233.1 2106.88  1255.7 2108.56
  1313.6 2109.51    1368 2115.12  1418.5 2126.81  1469.2 2125.91  1502.4 2134.49
  1603.7 2145.51  1667.1 2162.15  1699.9 2171.45  1754.6  2190.7  1925.2 2235.79
BR D #Mann= 17
       0    .016    60.7     .12   436.4     .06   492.2     .08   543.2     .12
   843.3     .08   900.9    .016   940.7     .08  1086.7    .035 1166.32     .06
  1255.7     .08  1313.6     .06    1368     .08  1418.5    .016  1502.4     .12
  1667.1    .016  1699.9     .12
BC Design=,, 0 ,, 0 ,,0,,,,
BC HTab HWMax=0
BC HTab TWMax=0
BC HTab MaxFlow=0
BC Use User HTab Curves=0
BC User HTab FreeFlow(D)= 0

Type RM Length L Ch R = 1 ,1490    ,383.7,367.2,345.6
BEGIN DESCRIPTION:
Merged US Survey CHE008BD
END DESCRIPTION:
XS GIS Cut Line= 3
     2087203.339      447539.108      2087837.02      447960.115
     2089000.214      448012.198
#Sta/Elev= 30
       0 2241.04    60.7 2232.78   104.9 2226.08   209.9 2196.88   436.4 2174.81
   492.2 2156.13   543.2 2147.27   580.4  2152.7   816.6 2122.41   843.3 2122.87
   900.9 2124.35   940.7 2123.65   993.7 2110.64  1046.1  2106.2  1086.7 2089.26
  1105.8 2086.79 1166.32 2089.31    1204 2095.71  1233.1 2106.88  1255.7 2108.56
  1313.6 2109.51    1368 2115.12  1418.5 2126.81  1469.2 2125.91  1502.4 2134.49
  1603.7 2145.51  1667.1 2162.15  1699.9 2171.45  1754.6  2190.7  1925.2 2235.79
#Mann= 17 ,-1 , 0
       0    .016       0    60.7     .12       0   436.4     .06       0
   492.2     .08       0   543.2     .12       0   843.3     .08       0
   900.9    .016       0   940.7     .08       0  1086.7     .04       0
 1166.32     .06       0  1255.7     .08       0  1313.6     .06       0
    1368     .08       0  1418.5    .016       0  1502.4     .12       0
  1667.1    .016       0  1699.9     .12       0
#XS Ineff= 2 , 0
         1024.84  2121.3 1260.76          2121.3
Permanent Ineff=
       F       F
#Block Obstruct= 4 ,-1
  501.35  540.322172.588  716.19  752.11 2156.75  752.72  763.192156.057
 1700.14    17402209.317
Bank Sta=1086.7,1166.32
XS Rating Curve= 0 ,0
Exp/Cntr=0.5,0.3

Type RM Length L Ch R = 1 ,1123    ,431.5,434.5,440.7
XS GIS Cut Line= 2
     2087498.478      448537.372     2088991.534      448151.087
#Sta/Elev= 30
       0 2371.04     9.8 2368.81    91.7 2325.05   229.2 2270.59   268.5 2246.77
   284.9 2242.33     334 2209.62   490.2 2160.39   504.2  2152.3   535.6 2143.25
   543.5 2139.05   585.8 2139.08   626.2 2134.33   641.8 2121.09   690.7 2117.94
   700.7 2115.73   726.9 2092.91   754.3 2086.97   792.1  2086.4   824.3 2086.74
   861.2 2091.54   887.4  2104.6  1021.6 2103.51  1080.5 2124.96  1104.5  2125.5
  1134.6 2126.12  1218.1 2128.06  1305.2 2142.34  1417.8  2169.5  1542.2 2210.99
#Mann= 11 ,-1 , 0
       0     .12       0   490.2     .06       0   535.6     .08       0
   585.8     .12       0   626.2    .016       0   690.7     .12       0
   754.3    .035       0   824.3     .12       0  1104.5     .08       0
  1134.6    .016       0  1305.2     .12       0
#XS Ineff= 2 , 0
                           890.6         2104.74
Permanent Ineff=
       F       F
#Block Obstruct= 2 ,-1
  533.67  581.232164.183  886.32   906.62128.187
Bank Sta=754.3,824.3
XS Rating Curve= 0 ,0
Exp/Cntr=0.3,0.1

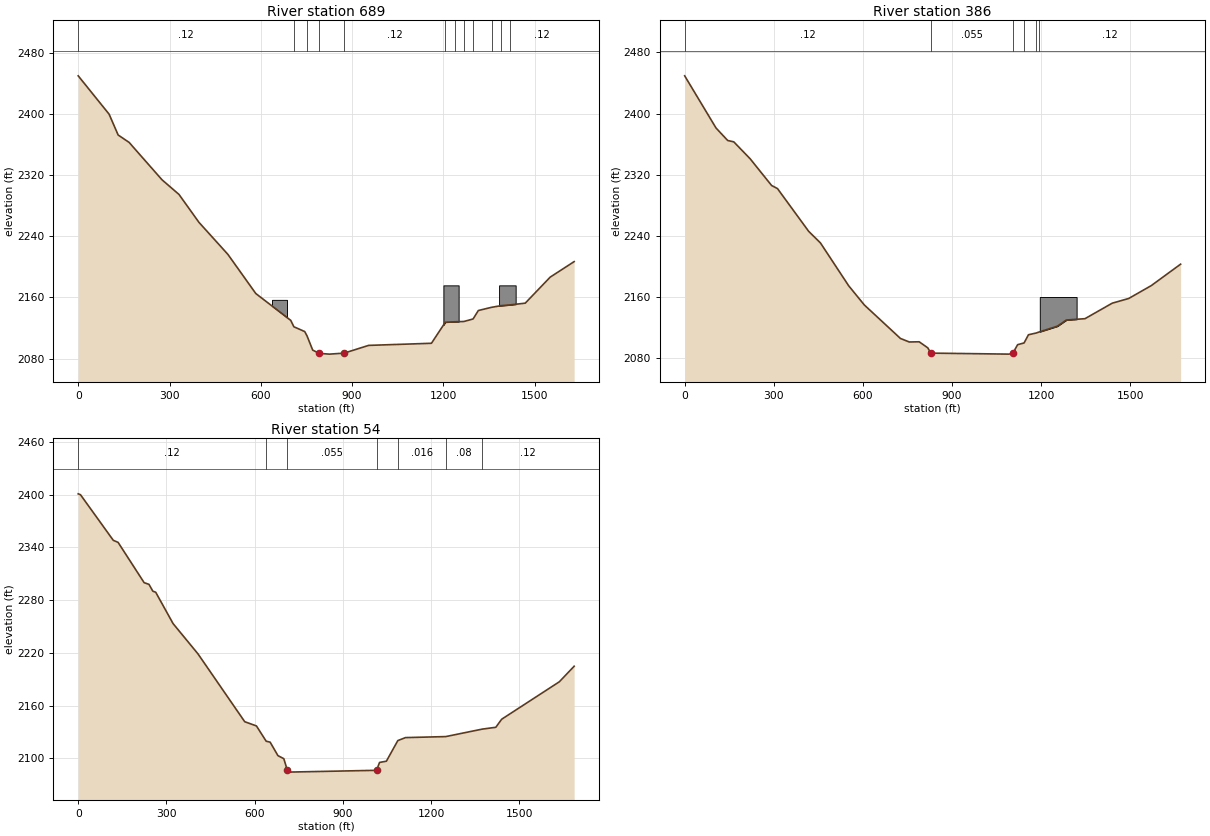
Type RM Length L Ch R = 1 ,689     ,282.7,302.7,342.7
XS GIS Cut Line= 2
     2087572.263      448949.698     2089156.464      448567.753
#Sta/Elev= 30
       0 2450.36   101.6 2400.08   131.2 2372.85   167.2 2363.17   275.4 2314.15
   331.2 2294.96   396.7 2258.45   491.8 2216.49   583.6 2165.16   698.4 2130.01
   708.6 2121.64   744.3 2115.36   751.9 2109.67   770.5 2091.06   792.4 2086.75
   825.9  2085.8   873.6 2087.09   954.2 2097.24  1160.7 2100.01  1206.3 2127.61
  1236.7 2128.17  1267.1 2128.52  1297.5 2131.87  1314.8 2142.94  1358.2 2147.11
  1388.6 2149.25    1419 2150.28  1468.9 2152.57  1550.9 2186.67  1629.6 2206.99
#Mann= 12 ,-1 , 0
       0     .12       0   708.6    .016       0   751.9     .12       0
   792.4     .04       0   873.6     .12       0  1206.3     .08       0
  1236.7    .016       0  1267.1     .12       0  1297.5     .08       0
  1358.2    .016       0  1388.6     .08       0    1419     .12       0
#Block Obstruct= 3 ,-1
  636.85  685.952156.894    1200    12502175.893 1382.94 1437.392175.893
Bank Sta=792.4,873.6
XS Rating Curve= 0 ,0
Exp/Cntr=0.3,0.1

Type RM Length L Ch R = 1 ,386     ,272.3,332.1,334.2
BEGIN DESCRIPTION:
Vegetation with in the channel bumped mannings n to 0.055
END DESCRIPTION:
XS GIS Cut Line= 4
2087606.72609851449080.8685015872088321.76941045 449040.27652318
2088758.91379329449009.0519244062089274.11967307449012.174384283
#Sta/Elev= 30
       0 2449.32   105.4 2381.14   144.8 2364.73   165.4 2362.93   220.4 2340.81
   292.7 2305.83   312.4 2301.85   417.6 2245.82     457 2230.77   552.3 2174.59
   604.9 2149.54   726.5 2105.72   756.1 2101.13   789.5 2101.37   818.6 2093.44
  828.58 2086.56 1091.97 2085.24 1104.81 2086.34    1121  2097.6  1142.7 2099.88
  1157.4 2110.57  1183.6 2112.87  1193.5 2114.22  1254.5 2121.73  1285.3 2129.91
  1347.7  2131.6  1439.5 2151.91  1494.8 2158.02  1570.8 2174.84  1669.7 2202.93
#Mann= 6 ,-1 , 0
       0     .12       0  828.58    .055       0 1104.81     .12       0
  1142.7    .016       0  1183.6     .08       0  1193.5     .12       0
#Block Obstruct= 1 ,-1
 1195.57 1319.56 2159.92
Bank Sta=828.58,1104.81
XS Rating Curve= 0 ,0
Exp/Cntr(USF)=0,0
Exp/Cntr=0.3,0.1

Type RM Length L Ch R = 1 ,54      ,54,54,54
BEGIN DESCRIPTION:
Vegetation with in the channel bumped mannings n to 0.055
END DESCRIPTION:
XS GIS Cut Line= 3
2087671.43221006449241.7904040452088165.15587813449245.887695896
2089343.12728534449436.411766976
#Sta/Elev= 30
       0 2400.91     7.7  2399.9   119.3 2348.02   135.7 2345.64   224.3  2299.8
   240.7 2297.91   253.8 2290.15   263.6 2288.92   322.7 2253.25   407.4 2218.78
   566.4 2141.59   606.3 2136.76   639.5 2119.34   652.8 2118.34   679.4 2102.97
   699.3 2099.52   711.3 2086.52   711.4  2084.2 1017.89 2086.28  1018.2 2089.14
    1025 2095.22  1048.3 2096.63  1087.2  2120.1  1113.3 2123.49  1250.3 2124.64
    1374 2133.13  1420.5 2135.22  1440.5  2144.4  1636.6 2187.01 1687.02  2204.7
#Mann= 7 ,-1 , 0
       0     .12       0   639.5    .016       0   711.3    .055       0
 1017.89     .12       0  1087.2    .016       0  1250.3     .08       0
    1374     .12       0
Bank Sta=711.3,1017.89
XS Rating Curve= 0 ,0
Exp/Cntr(USF)=0,0
Exp/Cntr=0.3,0.1
LCMann Table=0

Chan Stop Cuts=-1
Use User Specified Reach Order=0
Composite Channel Slope=5